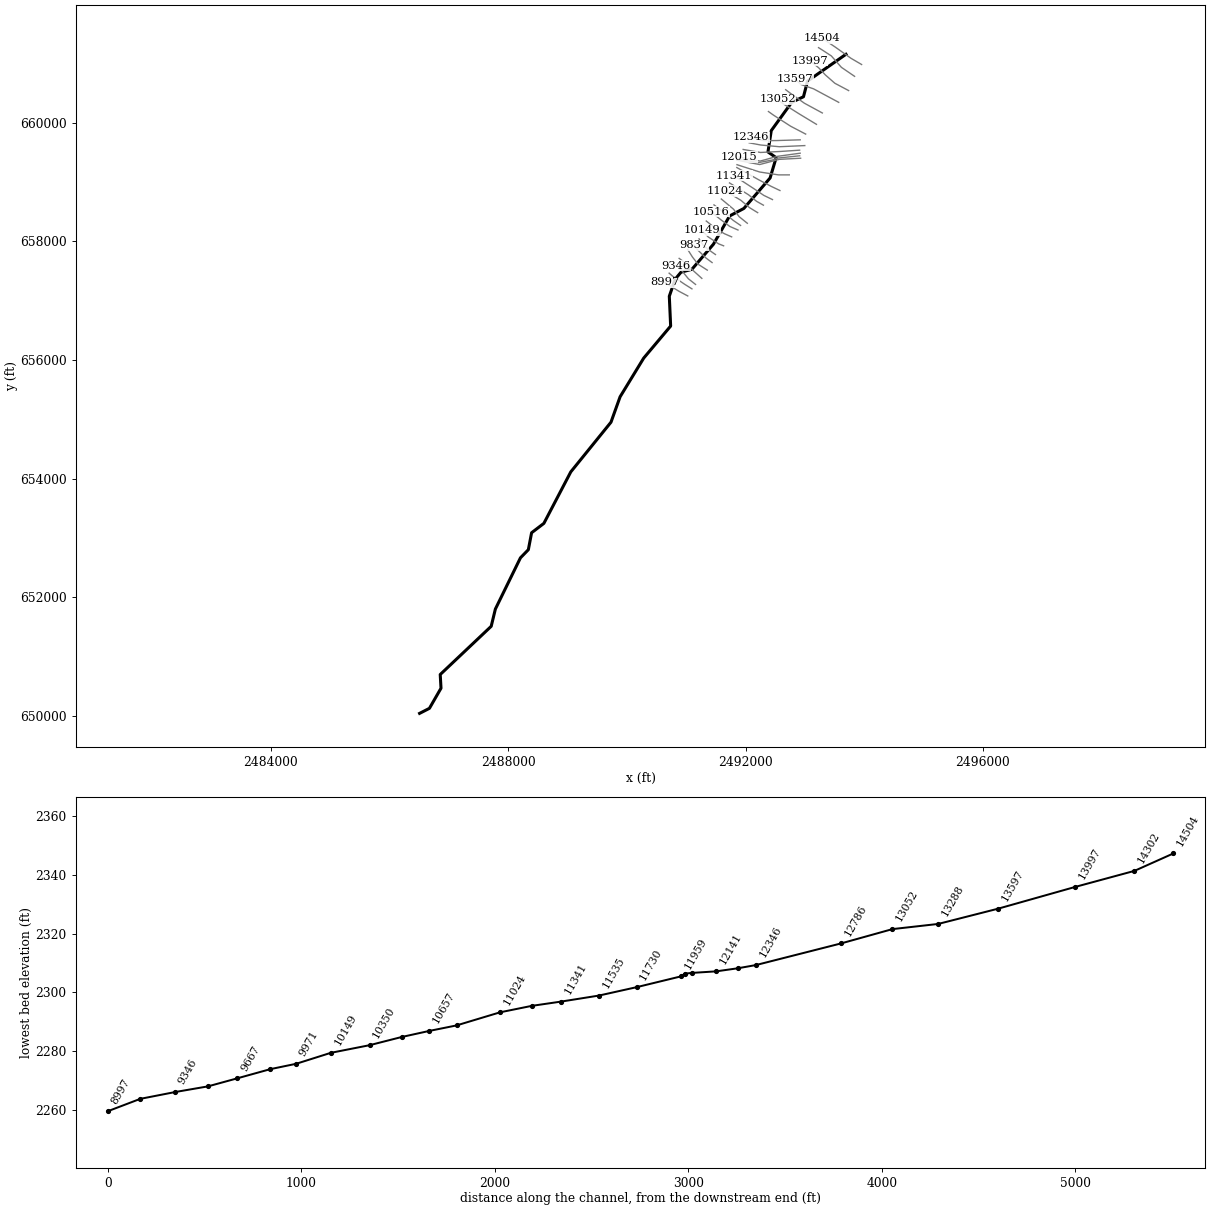
--- SHAVERN.prj (project) ---

Proj Title=SHAVERN
Current Plan=p01
Default Exp/Contr=0,0
English Units
Geom File=g01
Flow File=f01
Plan File=p01
Background Map Layer=QC
BEGIN DESCRIPTION:
Stream Name:Shaver Run
Flood Zone: Zone A
Pendleton County, WV
WVDHSEM Flood Warning & Analysis Mapping
HEC-RAS Version: 5.0.7
Hydrology Method:
Regression
Model Notes:
Tie in with South Branch Potomac River at the downstream end.
END DESCRIPTION:
DSS File=dss
DSS Export Rating Curves= 0
DSS Export Rating Curve Sorted= 0
DSS Export Volume Flow Curves= 0
DXF OffsetX= 0
DXF OffsetY= 0
DXF ScaleX= 0
DXF ScaleY= 0

--- SHAVERN.p01 (plan) ---

Plan Title=Floodplain
Program Version=5.07
Short Identifier=Floodplain
Geom File=g01
Flow File=f01
Subcritical Flow
K Sum by GR= 0
Std Step Tol= 0.01
Critical Tol= 0.01
Num of Std Step Trials= 20
Max Error Tol= 0.3
Flow Tol Ratio= 0.001
Split Flow NTrial= 30
Split Flow Tol= 0.02
Split Flow Ratio= 0.02
Log Output Level= 0
Friction Slope Method= 1
Unsteady Friction Slope Method= 2
Unsteady Bridges Friction Slope Method= 1
Parabolic Critical Depth
Global Vel Dist= 0 , 0 , 0
Global Log Level= 0
CheckData=True
Encroach Param=-1 ,0,0, 0
Computation Interval=0.1SEC
Output Interval=1MIN
Instantaneous Interval=Max Profile
Mapping Interval=1HOUR
Computation Time Step Use Courant=        0
Computation Time Step Use Time Series=    0
Computation Time Step Count To Double=0
Computation Time Step Max Doubling=0
Computation Time Step Max Halving=0
Computation Time Step Residence Courant=0
Run HTab= 0
Run UNet= 0
Run Sediment= 0
Run PostProcess= 0
Run WQNet= 0
Run RASMapper= 0
UNET Theta= 0
UNET Theta Warmup= 0
UNET ZTol= 0
UNET ZSATol= 0
UNET MxIter= 0
UNET Max Iter WO Improvement= 0
UNET MaxInSteps= 0
UNET DtIC= 0
UNET DtMin= 0
UNET MaxCRTS= 0
UNET WFStab= 0
UNET SFStab= 0
UNET WFX= 1
UNET SFX= 1
UNET 1D Methodology=Finite Difference
UNET DSS MLevel= 1
UNET Pardiso=0
UNET DZMax Abort= 0
UNET Use Existing IB Tables= 0
UNET Froude Reduction=False
UNET Froude Limit= 0
UNET Froude Power= 0
UNET D1 Cores= 0
UNET D2 Coriolis=0
UNET D2 Cores= 0
UNET D2 Theta= 1
UNET D2 Theta Warmup= 1
UNET D2 Z Tol= 0.01
UNET D2 Volume Tol= 0.01
UNET D2 Max Iterations= 20
UNET D2 Equation= 0
UNET D2 RampUpFraction=0.1
UNET D2 TimeSlices= 1
UNET D2 BCVolumeCheck=0
UNET D1D2 MaxIter= 0
UNET D1D2 ZTol=0.01
UNET D1D2 QTol=0.1
UNET D1D2 MinQTol=1
DSS File=dss
Write IC File= 0
Write IC File at Fixed DateTime=0
Write IC File at Sim End=0
Echo Input=False
Echo Parameters=False
Echo Output=False
Write Detailed= 0
HDF Write Warmup=0
HDF Write Time Slices=0
HDF Flush=0
HDF Face Node Velocities=0
HDF Compression= 1
HDF Chunk Size= 1
HDF Spatial Parts= 1
HDF Use Max Rows=0
HDF Fixed Rows= 1
Calibration Method= 0
Calibration Iterations= 20
Calibration Max Change=0.05
Calibration Tolerance=0.2
Calibration Maximum=1.5
Calibration Minimum=0.5
Calibration Optimization Method= 1
WQ AD Non Conservative
WQ ULTIMATE=-1
WQ Max Comp Step=1HOUR
WQ Output Interval=15MIN
WQ Output Selected Increments= 0
WQ Output face flow=0
WQ Output face velocity=0
WQ Output face area=0
WQ Output face dispersion=0
WQ Output cell volume=0
WQ Output cell surface area=0
WQ Output cell continuity=0
WQ Output cumulative cell continuity=0
WQ Output face conc=0
WQ Output face dconc_dx=0
WQ Output face courant=0
WQ Output face peclet=0
WQ Output face adv mass=0
WQ Output face disp mass=0
WQ Output cell mass=0
WQ Output cell source sink temp=0
WQ Output nsm pathways=0
WQ Output nsm derived pathways=0
WQ Output MaxMinRange=-1
WQ Daily Max Min Mean=-1
WQ Daily Range=0
WQ Daily Time=0
WQ Create Restart=0
WQ Fixed Restart=0
WQ System Summary=0
WQ Write To DSS=0
WQ Use Fixed Temperature=0
Sorting and Armoring Iterations= 10
XS Update Threshold= 0.02
Bed Roughness Predictor= 0
Hydraulics Update Threshold= 0.02
Energy Slope Method= 1
Volume Change Method= 1
Sediment Retention Method= 0
XS Weighting Method= 0
Number of US Weighted Cross Sections= 1
Number of DS Weighted Cross Sections= 1
Upstream XS Weight=0
Main XS Weight=1
Downstream XS Weight=0
Number of DS XS's Weighted with US Boundary= 1
Upstream Boundary Weight= 1
Weight of XSs Associated with US Boundary= 0
Number of US XS's Weighted with DS Boundary= 1
Downstream Boundary Weight= 0.5
Weight of XSs Associated with DS Boundary= 0.5
Percentile Method= 0
Sediment Output Level= 3
Mass or Volume Output= 0
Output Increment Type= 1
Profile and TS Output Increment= 1
XS Output Flag= 0
XS Output Increment= 10
Write Gradation File= 0
Read Gradation Hotstart= 0
Write HDF5 File= 1
Write Binary Output= 1
Write DSS Sediment File= 0
SV Curve= 0
Specific Gage Flag= 0

--- SHAVERN.f01 (steady flow) ---

Flow Title=Flows
Program Version=5.07
Number of Profiles= 6
Profile Names=P100yr,P10yr,P25yr,P50yr,P500yr,P101yr
River Rch & RM=SHAVERN,Main            ,14504
     547     256     362     452     802     666
River Rch & RM=SHAVERN,Main            ,13597
     610     285     403     503     894     742
River Rch & RM=SHAVERN,Main            ,9346
     798     371     526     658    1173     971
River Rch & RM=SHAVERN,Main            ,6902
    1073     497     706     884    1583    1306
River Rch & RM=SHAVERN,Main            ,4864
    1204     557     791     991    1778    1465
River Rch & RM=SHAVERN,Main            ,0
    1317     608     865    1084    1947    1603
Boundary for River Rch & Prof#=SHAVERN,Main            , 1
Up Type= 0
Dn Type= 1
Dn Known WS=2061.44
Boundary for River Rch & Prof#=SHAVERN,Main            , 2
Up Type= 0
Dn Type= 1
Dn Known WS=2059.95
Boundary for River Rch & Prof#=SHAVERN,Main            , 3
Up Type= 0
Dn Type= 1
Dn Known WS=2060.6
Boundary for River Rch & Prof#=SHAVERN,Main            , 4
Up Type= 0
Dn Type= 1
Dn Known WS=2061.03
Boundary for River Rch & Prof#=SHAVERN,Main            , 5
Up Type= 0
Dn Type= 1
Dn Known WS=2062.35
Boundary for River Rch & Prof#=SHAVERN,Main            , 6
Up Type= 0
Dn Type= 1
Dn Known WS=2061.9
DSS Import GetInterval= 0
DSS Import GetPeak= 0
DSS Import FillOption= 0

--- SHAVERN.g01 (geometry) ---

Geom Title=Geometry
Program Version=5.07

River Reach=SHAVERN         ,Main
Reach XY= 30
2493691.53200001661154.9689999972493044.05200002660702.561000019
2492975.65099999 660439.130000012492776.90800002660343.892000005
2492432.67300004659867.6979999992492376.98100001659508.273000017
2492515.16700695659411.7808049662492413.34900001659069.458000019
2491971.26499999658555.6600000112491730.67000002658428.572000012
2491458.43200001657952.5020000042491095.06200004657528.825000003
2490912.03000003657480.6389999992490814.38699999 657363.51000002
2490714.45600003657074.8850000052490737.06300002656571.982000008
2490282.81500003 656031.49000001     2489885.021655378.997000009
2489731.45300004654950.6290000082489054.23699999654113.225999996
2488600.36600003653244.3390000162488393.52700001653086.409000009
2488338.91200003652800.8110000192488205.67100003652663.481000021
2487783.17200002651799.6070000082487712.83400002651508.829000011
2486853.78600001650695.8410000212486866.75700003650464.665000021
2486671.81300002650125.4050000162486505.99138936650040.371641606

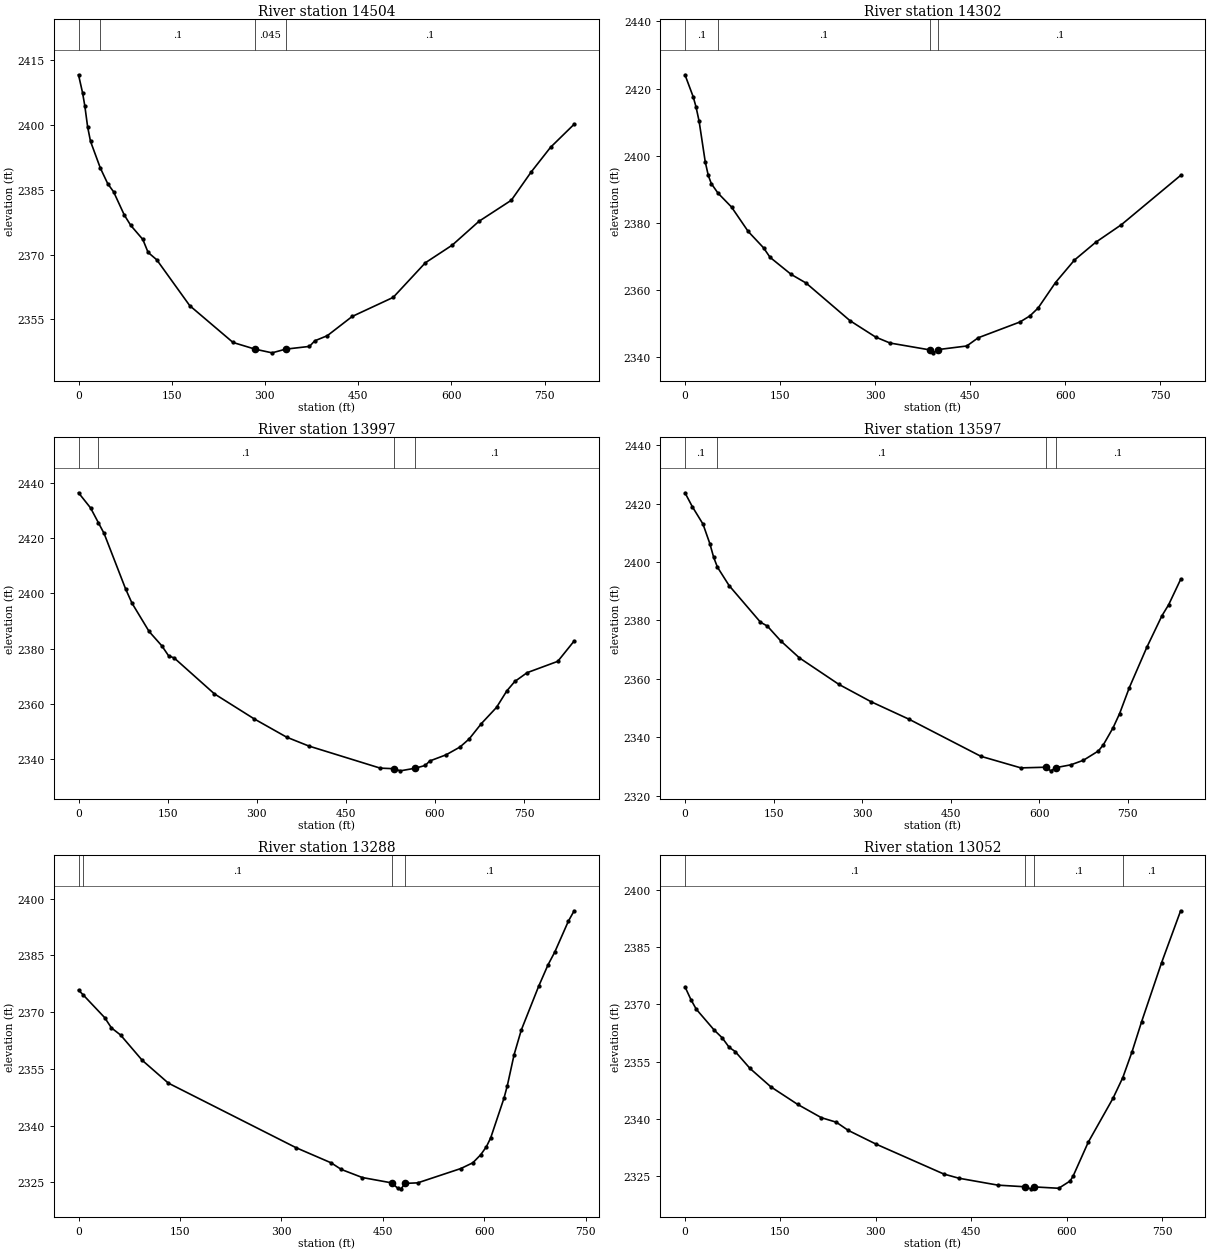
Type RM Length L Ch R = 1 ,14504   ,201.6,201.6,201.6
XS GIS Cut Line= 4
2493955.43182016660982.6878855952493777.11346875 661086.85405127
2493517.58081868661272.2345156072493291.59320501 661424.06994354
#Sta/Elev= 30
       0 2411.67     6.5 2407.51    10.1 2404.51    14.7 2399.58    19.3 2396.26
   35.112390.071    47.1 2386.42    56.4 2384.58    73.8 2379.15    84.2 2376.76
   103.5 2373.53     112 2370.52   125.9 2368.82     179 2358.19   248.7 2349.66
  284.162348.113   311.5 2347.26  333.322348.113   371.7 2348.75   380.3 2350.05
   400.4 2351.23   440.5 2355.69   506.5 2360.11   558.2 2368.12   601.5 2372.21
   644.5 2377.73   696.6 2382.61   728.3 2389.11   759.7 2394.87797.7126 2400.22
#Mann= 4 ,-1 , 0
       0      .1       0   35.11      .1       0  284.16    .045       0
  333.32      .1       0
Bank Sta=284.16,333.32
XS Rating Curve= 0 ,0
Exp/Cntr(USF)=0,0
Exp/Cntr=0.3,0.1

Type RM Length L Ch R = 1 ,14302   ,302.4,305.4,302.8
XS GIS Cut Line= 5
2493837.14142863660783.1831954042493614.68487142660935.018623337
2493445.19416117661127.461200601 2493302.1863744661221.034196885
 2493229.7997169661266.937930911
#Sta/Elev= 30
       0 2424.12      13 2417.55    17.4 2414.57    22.3  2410.3      32 2398.17
    36.8 2394.14    41.6  2391.7   52.162388.872    73.5 2384.73    99.8 2377.46
     124  2372.6   134.3 2369.76   167.6 2364.68   191.1 2362.11   260.6 2350.88
   301.1    2346   323.7 2344.24   386.4  2342.2   391.8 2341.32   399.6 2342.29
   444.8 2343.36   462.9 2345.81   528.7  2350.5   544.5 2352.32   557.4 2354.66
   584.9 2362.26   614.7 2368.93   648.2 2374.22   688.9 2379.48782.3892 2394.16
#Mann= 4 ,-1 , 0
       0      .1       0   52.16      .1       0   386.4    .045       0
   399.6      .1       0
Bank Sta=386.4,399.6
XS Rating Curve= 0 ,0
Exp/Cntr(USF)=0,0
Exp/Cntr=0.3,0.1

Type RM Length L Ch R = 1 ,13997   ,393.5,399.7,397.6
XS GIS Cut Line= 6
2493736.70248922 660543.16338616 2493504.2049443660666.677706902
2493346.78473159660804.7231242022493230.53595912660928.237444943
 2493145.7712292 660996.049228882493077.95944526661044.486217406
#Sta/Elev= 30
       0  2436.4    20.3 2430.92   33.452425.571      43 2421.72    79.2 2401.67
      90  2396.5   118.8 2386.26   140.3 2381.05   151.7 2377.44     161 2376.69
   228.7 2363.71   295.6 2354.67   350.3 2348.05   387.6 2344.85   507.7 2336.86
   530.8 2336.65   541.5 2335.88  566.242336.815   583.6 2337.83     591 2339.44
   618.5 2341.66     642 2344.49   657.4  2347.4   678.1 2352.99   703.5 2358.82
   720.8 2364.78   734.2 2368.18     755 2371.37   806.6 2375.47 834.146 2382.83
#Mann= 4 ,-1 , 0
       0      .1       0   33.45      .1       0   530.8    .045       0
  566.24      .1       0
Bank Sta=530.8,566.24
XS Rating Curve= 0 ,0
Exp/Cntr(USF)=0,0
Exp/Cntr=0.3,0.1

Type RM Length L Ch R = 1 ,13597   ,308.6,309.3,255.8
XS GIS Cut Line= 4
2493569.59487881660344.571733203 2493145.7712292660572.225579276
2492930.22663026660647.3029114912492835.77450263660736.911340265
#Sta/Elev= 30
       0 2423.76    12.3 2419.05    30.5 2413.03    42.2 2406.28    48.6 2401.63
   54.96 2398.28    74.7 2391.97   127.9  2379.4   139.5 2378.08   162.2    2373
   193.9 2367.16   260.8 2358.08   315.2 2352.15   380.1 2346.09   501.2 2333.44
     569 2329.47   610.8  2329.7   619.8 2328.46   628.3 2329.56   653.7 2330.53
   674.9 2332.09   700.3 2335.28   708.8 2337.44   725.2 2343.25   736.2  2348.1
   752.7 2357.01   782.2 2370.77   807.9 2381.62   819.2 2385.38839.5366 2394.07
#Mann= 4 ,-1 , 0
       0      .1       0   54.96      .1       0   610.8    .045       0
   628.3      .1       0
Bank Sta=610.8,628.3
XS Rating Curve= 0 ,0
Exp/Cntr(USF)=0,0
Exp/Cntr=0.3,0.1

Type RM Length L Ch R = 1 ,13288   ,232.5,235.9,215.8
XS GIS Cut Line= 4
2493293.50404421660165.3548756562492990.77286592660330.040636645
2492755.85347157 660497.14824706 2492675.9324405660557.694482718
#Sta/Elev= 30
       0 2375.82    7.13  2374.5    38.6 2368.55    48.7 2365.82    62.2 2363.94
    94.2 2357.26   132.9 2351.22   321.7 2334.16   373.7 2330.15   388.8  2328.4
   419.8 2326.27   463.4 2324.85   472.3 2323.42   477.2 2323.28   482.9 2324.72
   501.7 2324.86   565.6 2328.65   583.3 2330.17     595  2332.3   603.4 2334.43
   609.7 2336.75   629.4 2347.25   634.3 2350.54   644.3 2358.72   654.9 2365.22
   680.6 2376.79   694.5 2382.48   704.6  2385.9   724.6 2394.02733.1841 2396.77
#Mann= 4 ,-1 , 0
       0      .1       0    7.13      .1       0   463.4    .045       0
   482.9      .1       0
Bank Sta=463.4,482.9
XS Rating Curve= 0 ,0
Exp/Cntr(USF)=0,0
Exp/Cntr=0.3,0.1

Type RM Length L Ch R = 1 ,13052   ,263.7,265.3,250.6
XS GIS Cut Line= 4
2493194.20821773659974.028770978  2492906.008136660148.401929672
2492637.18284968660317.931389513 2492537.8870232660393.008721729
#Sta/Elev= 30
       0 2374.64     9.4 2371.25    17.7 2368.76    46.1 2363.23    58.5 2361.23
    69.5 2358.72    78.9 2357.63   102.2 2353.18     135 2348.34     177 2343.74
   214.4 2340.23   237.8 2339.05   256.6  2336.9   300.3 2333.29   406.9 2325.42
   430.6 2324.32     492  2322.5   534.6 2322.07     544 2321.53   548.8 2322.04
   587.5 2321.68   605.5  2323.6   610.3 2324.94   633.9 2333.78   672.8 2345.32
  688.212350.756   702.9 2357.63   717.9 2365.51   749.1 2380.92779.1465 2394.62
#Mann= 4 ,-1 , 0
       0      .1       0   534.6    .045       0   548.8      .1       0
  688.21      .1       0
Bank Sta=534.6,548.8
XS Rating Curve= 0 ,0
Exp/Cntr(USF)=0,0
Exp/Cntr=0.3,0.1

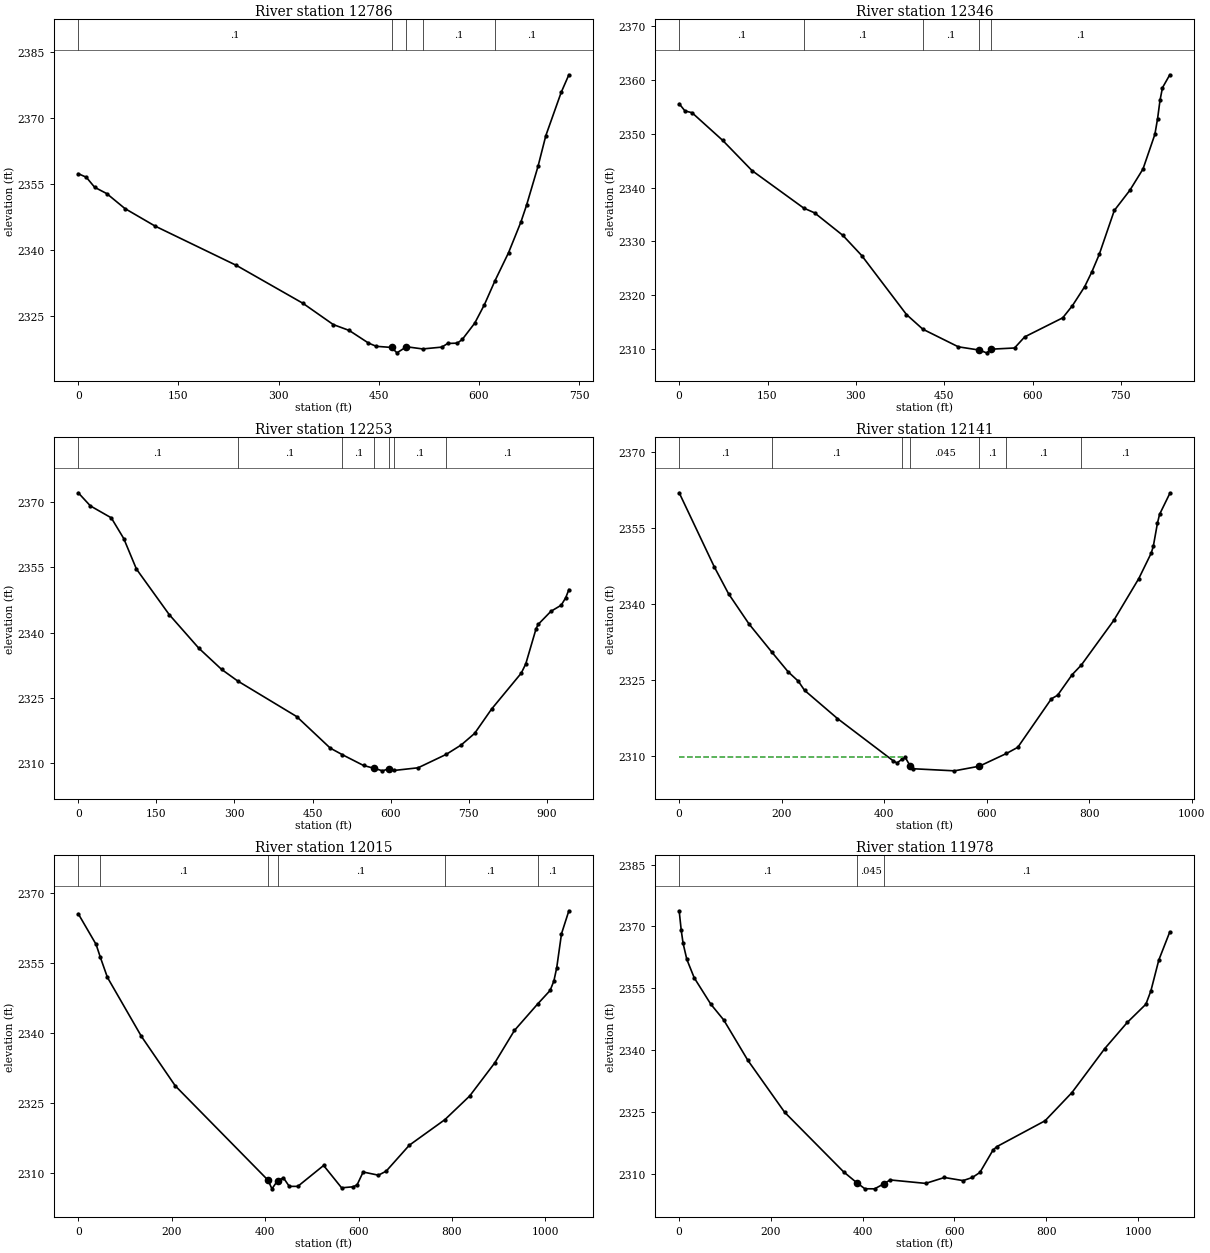
Type RM Length L Ch R = 1 ,12786   ,432.8,440.1,442.4
XS GIS Cut Line= 4
2493012.56951076659809.3430099882492758.27532099659942.544728435
2492470.07523926660129.0271342612492385.31050934660189.573369919
#Sta/Elev= 30
       0  2357.3      12  2356.5    24.6 2354.21    42.7 2352.78    69.8  2349.4
   115.1 2345.41   236.9 2336.49   336.2 2327.92   381.8 2323.08   405.6 2321.75
   434.5 2318.89   446.1 2318.15  469.022317.895   477.1 2316.67   491.4 2318.05
  515.592317.555   544.4 2317.97   553.1  2318.8   567.5 2318.87   574.9 2319.71
   593.6 2323.41   608.1 2327.61  624.052333.072   644.3 2339.42   662.7 2346.34
   671.1 2350.13   688.3 2358.95     700 2365.93     723 2375.74 734.507 2379.73
#Mann= 5 ,-1 , 0
       0      .1       0  469.02    .045       0   491.4      .1       0
  515.59      .1       0  624.05      .1       0
Bank Sta=469.02,491.4
XS Rating Curve= 0 ,0
Exp/Cntr(USF)=0,0
Exp/Cntr=0.5,0.3

Type RM Length L Ch R = 1 ,12346   ,95.4,93.2,83.7
XS GIS Cut Line= 4
2492920.53923256659712.4690329362492525.77777607659700.359785805
2492310.23317713659697.9379363782492094.68857818659753.640473183
#Sta/Elev= 30
       0 2355.55     9.8 2354.22    21.8 2353.89    73.8 2348.76   123.6 2343.15
  211.482336.184   229.9  2335.3   277.9 2331.12   309.9 2327.38     386 2316.42
  413.74  2313.7     474 2310.43   509.8 2309.82   521.9 2309.31   529.9 2309.99
   569.5 2310.21   586.7 2312.27   651.3 2315.81   667.8 2318.07   688.5 2321.58
   700.9 2324.37   713.3 2327.58   738.9 2335.74   765.2 2339.47   787.6 2343.43
   807.8 2349.87   812.4 2352.79   816.5 2356.18   820.7 2358.53833.1312 2360.93
#Mann= 5 ,-1 , 0
       0      .1       0  211.48      .1       0  413.74      .1       0
   509.8    .045       0   529.9      .1       0
#XS Ineff= 2 , 0
             446  2309.7     600          2309.7
Permanent Ineff=
       F       F
Bank Sta=509.8,529.9
XS Rating Curve= 0 ,0
Exp/Cntr(USF)=0,0
Exp/Cntr=0.5,0.3

Type RM Length L Ch R = 1 ,12253   ,106.3,111.9,118.4
XS GIS Cut Line= 4
 2492998.0384142659615.5950558842492569.37106574659596.220260473
2492254.53064032659625.2824535892492060.78268622659661.610194984
#Sta/Elev= 30
       0 2372.16    23.3 2369.14    63.4  2366.4    87.4 2361.63   111.7 2354.63
   174.7 2344.15   231.5 2336.43   275.3 2331.55  306.092328.896   419.7 2320.69
     484 2313.45   507.5 2311.92     548 2309.45  568.732308.789   584.4 2308.22
   596.4 2308.69  607.052308.313   652.7 2308.92   706.62311.992   735.5 2314.16
   761.3 2316.82   793.9 2322.42   850.9 2330.68   859.6 2332.81   879.4  2340.9
   883.4 2341.89   907.9  2344.9   927.7 2346.31   936.3 2348.02942.4081 2349.89
#Mann= 7 ,-1 , 0
       0      .1       0  306.09      .1       0   507.5      .1       0
  568.73    .045       0   596.4      .1       0  607.05      .1       0
   706.6      .1       0
Bank Sta=568.73,596.4
XS Rating Curve= 0 ,0
Exp/Cntr(USF)=0,0
Exp/Cntr=0.5,0.3

Type RM Length L Ch R = 1 ,12141   ,93.7,126.3,126.4
XS GIS Cut Line= 4
2492910.85183485659538.095874242 2492583.9021623659516.299229405
2492252.10879089659499.3462834212491959.06501031659550.205121373
#Sta/Elev= 30
       0  2361.9    68.3 2347.36    96.3 2342.03   136.4 2336.06  180.982330.519
   212.6 2326.66   232.4 2324.82   244.6 2323.02   308.8 2317.47   417.8 2309.13
     425 2308.72  435.422309.503     441 2309.83  451.052308.083     457 2307.58
   537.1 2307.17   585.72308.083  638.592310.587   660.7  2311.8   726.2 2321.34
   738.4 2322.05   766.8  2326.1  784.68 2327.99     848 2336.78   896.8 2345.01
   921.1 2350.03   925.2 2351.39   933.3 2355.96   937.4 2357.66 957.326 2361.77
#Mann= 7 ,-1 , 0
       0      .1       0  180.98      .1       0  435.42      .1       0
  451.05    .045       0   585.7      .1       0  638.59      .1       0
  784.68      .1       0
#XS Ineff= 2 , 0
          439.39 2309.84
Permanent Ineff=
       F       F
Bank Sta=451.05,585.7
XS Rating Curve= 0 ,0
Exp/Cntr(USF)=0,0
Exp/Cntr=0.3,0.1

Type RM Length L Ch R = 1 ,12015   ,62.8,36.6,27.9
XS GIS Cut Line= 4
2492920.53923255659487.2370362892492535.46517377659433.956348911
2492244.84324261659354.0353178422491891.25322637659421.847101779
#Sta/Elev= 30
       0 2365.49    38.2 2358.93   47.11 2356.23    62.4 2351.88   135.1 2339.27
   207.6 2328.68   406.1  2308.5   414.6 2306.64   426.8  2308.4   439.3 2308.98
   451.7 2307.17   469.9 2307.17   525.2 2311.64   563.7 2306.86   588.6 2307.08
   596.9  2307.5   609.8 2310.24   642.5 2309.56   659.1 2310.42   708.6 2315.97
  784.762321.442   837.9 2326.51   891.9 2333.64   933.6 2340.52  983.472346.204
    1010 2349.08  1018.1 2351.11  1024.2 2353.96  1034.4 2361.211050.187 2366.13
#Mann= 6 ,-1 , 0
       0      .1       0   47.11      .1       0   406.1    .045       0
   426.8      .1       0  784.76      .1       0  983.47      .1       0
Bank Sta=406.1,426.8
XS Rating Curve= 0 ,0
Exp/Cntr(USF)=0,0
Exp/Cntr=0.3,0.1

Type RM Length L Ch R = 1 ,11978   ,20,19.6,27.3
XS GIS Cut Line= 5
2492911.32900641  659443.28728032492547.42507115659405.322747614
2492451.12479311659371.9880359872492213.15199066659327.541753817
2491859.43366173659391.433284436
#Sta/Elev= 30
       0 2373.81     4.5 2369.04     8.6 2365.88    16.7 2362.01    32.8 2357.55
      69 2351.15    97.1 2347.33   149.4 2337.59   229.8 2324.96   358.5 2310.49
   387.2 2307.85   404.7  2306.4   425.9 2306.38     447 2307.65   459.7 2308.54
   537.3  2307.7     578 2309.13   618.7 2308.38   639.1 2309.14   655.4 2310.35
   683.8 2315.74   691.9 2316.59   797.5 2322.89     856 2329.72   927.7 2340.41
   976.5 2346.72  1017.2 2351.15  1028.1 2354.39  1045.3 2361.85  1069.3 2368.69
#Mann= 3 , 0 , 0
       0      .1       0   387.2    .045       0     447      .1       0
Bank Sta=387.2,447
XS Rating Curve= 0 ,0
Exp/Cntr(USF)=0,0
Exp/Cntr=0.3,0.1

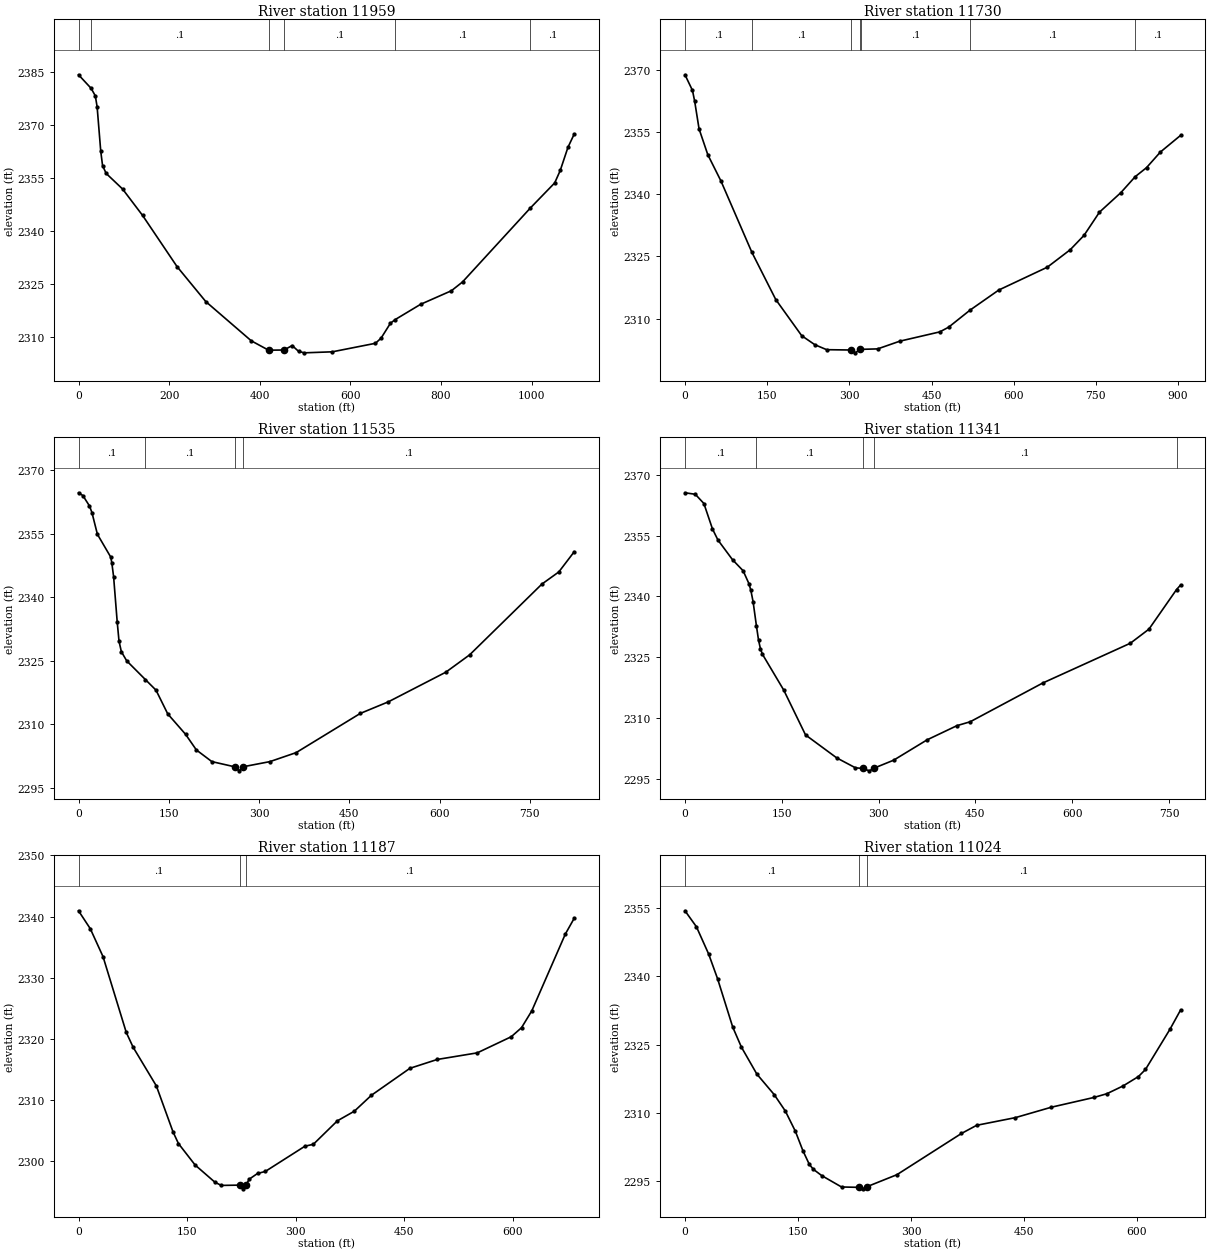
Type RM Length L Ch R = 1 ,11959   ,228.6,228.5,179.7
XS GIS Cut Line= 4
2492927.80478083659402.4723063692492566.94921631659383.097510958
2492237.57769434659295.9109316112491852.50363555  659368.5664144
#Sta/Elev= 30
       0  2384.1   27.762380.274    37.1 2378.14    41.1 2375.02    49.1 2362.44
    53.1  2358.4    61.1 2356.19    97.2  2351.8   141.3 2344.34   217.4 2329.86
   280.9 2319.96   381.3 2308.86   419.5 2306.21  453.48 2306.26   471.6 2307.52
   485.7 2305.88   498.1 2305.46   560.2 2305.75   655.4 2308.16   667.8 2309.62
   688.5 2313.84  699.222314.886     755 2319.18     823 2323.02   847.5  2325.5
  997.512346.455    1051 2353.52  1063.2 2357.03  1080.3  2363.61093.959  2367.3
#Mann= 6 ,-1 , 0
       0      .1       0   27.76      .1       0   419.5    .045       0
  453.48      .1       0  699.22      .1       0  997.51      .1       0
Bank Sta=419.5,453.48
XS Rating Curve= 0 ,0
Exp/Cntr(USF)=0,0
Exp/Cntr=0.3,0.1

Type RM Length L Ch R = 1 ,11730   ,197.3,195.3,169.4
XS GIS Cut Line= 4
2492736.47867615659121.5377729172492552.41811976659121.537772917
2492237.57769434659169.9747614432491854.92548498659293.489082185
#Sta/Elev= 30
       0 2368.73    13.7 2364.96    17.7 2362.35    25.7 2355.71    41.7 2349.48
    65.7 2343.15  122.072326.007   165.7 2314.63   213.1 2305.92   237.1 2303.75
   258.6 2302.56   303.1 2302.48   311.2  2301.8   319.3 2302.67   321.52302.641
   351.7 2302.75   392.2 2304.61     465 2306.84   481.3 2307.98  520.342312.084
   572.8 2316.92   661.3 2322.41   703.1 2326.61   728.4 2330.08   756.6 2335.67
   795.6 2340.36  821.742344.197   842.4 2346.37   867.8 2350.14904.6978 2354.15
#Mann= 7 ,-1 , 0
       0      .1       0  122.07      .1       0   303.1    .045       0
   319.3      .1       0   321.5      .1       0  520.34      .1       0
  821.74      .1       0
Bank Sta=303.1,319.3
XS Rating Curve= 0 ,0
Exp/Cntr(USF)=0,0
Exp/Cntr=0.3,0.1

Type RM Length L Ch R = 1 ,11535   ,193.8,193.7,180.6
XS GIS Cut Line= 4
2492579.05846344658857.5561854492492431.32564844658927.789818812
2492220.62474835659039.1948924222491852.50363555659245.052093658
#Sta/Elev= 30
       0 2364.64     7.2 2363.99    18.1 2361.56    22.3 2359.98    31.4 2354.83
    53.5 2349.46    55.3 2348.14    58.3 2344.85    64.3 2334.13    67.3 2329.59
    71.2 2327.09    80.1 2324.93  111.082320.512   128.8    2318   148.3 2312.39
   177.8 2307.59   195.9 2303.87   221.6 2301.12   259.3  2299.9   266.9 2298.94
   272.7 2299.88   318.1 2301.12   361.6 2303.24   468.2  2312.5   514.8 2315.24
   610.3 2322.24     650 2326.35   770.1 2343.07   798.2 2345.94823.6885 2350.69
#Mann= 4 ,-1 , 0
       0      .1       0  111.08      .1       0   259.3    .045       0
   272.7      .1       0
Bank Sta=259.3,272.7
XS Rating Curve= 0 ,0
Exp/Cntr(USF)=0,0
Exp/Cntr=0.3,0.1

Type RM Length L Ch R = 1 ,11341   ,154.6,154,141.7
XS GIS Cut Line= 4
2492453.12229328658704.979671591 2492307.8113277658775.213304954
2492135.86001843658891.462077417 2491801.6447976659109.428525785
#Sta/Elev= 30
       0 2365.59      16 2365.22    29.3 2362.94    42.6 2356.66    51.1 2353.91
    73.7 2349.05    90.1 2346.33    99.1 2343.14     102 2341.54   105.5 2338.72
  110.692332.739     114 2329.16     117 2327.02     120 2325.71     153 2316.86
   186.8 2305.78   235.1 2300.11   264.1 2297.66   275.1  2297.5   285.8 2296.91
     293 2297.58   323.3 2299.54   375.2 2304.57   421.4 2308.07   441.9 2309.03
   554.3  2318.6   690.1 2328.43   718.9 2331.91  761.582341.676 767.964 2342.82
#Mann= 5 ,-1 , 0
       0      .1       0  110.69      .1       0   275.1    .045       0
     293      .1       0  761.58      .1       0
Bank Sta=275.1,293
XS Rating Curve= 0 ,0
Exp/Cntr(USF)=0,0
Exp/Cntr=0.3,0.1

Type RM Length L Ch R = 1 ,11187   ,163.1,163.5,156.6
XS GIS Cut Line= 4
2492300.54577942658610.5275439652492184.29700696658675.917478476
2492051.09528851 658784.900702662491728.98931481658985.914205043
#Sta/Elev= 30
       0 2340.95    16.3 2338.01    33.9 2333.44      66 2321.04    75.5 2318.61
   107.6 2312.28   130.6 2304.77   138.1 2302.85   161.2 2299.33   188.6 2296.51
   197.4 2295.99   223.2 2296.04   227.6 2295.43  231.48 2296.06   236.1 2297.02
   247.5 2297.95   258.1 2298.27     313 2302.41   324.6 2302.72   357.8 2306.56
   381.3 2308.14   404.9 2310.75   458.1 2315.16   495.9 2316.61   551.2 2317.69
   598.2 2320.33   612.4 2321.81   626.6 2324.57     673 2337.15685.1648 2339.71
#Mann= 3 ,-1 , 0
       0      .1       0   223.2    .045       0  231.48      .1       0
Bank Sta=223.2,231.48
XS Rating Curve= 0 ,0
Exp/Cntr(USF)=0,0
Exp/Cntr=0.3,0.1

Type RM Length L Ch R = 1 ,11024   ,226,224.7,210.9
XS GIS Cut Line= 4
2492203.67180237658484.5913737972492065.62638507658569.356103718
2491920.31541949 658692.870424462491658.75568145 658850.29063717
#Sta/Elev= 30
       0 2354.47    15.2 2350.95    31.4 2344.96    43.3 2339.49    63.4 2328.85
      75 2324.42    95.4 2318.51   118.4    2314   133.2 2310.38   146.6  2305.9
   156.5 2301.66   165.1 2298.61   170.5 2297.53   181.5 2296.16   207.8 2293.65
   230.4 2293.57   236.1 2293.24   241.7 2293.72   281.3 2296.35     367 2305.43
   387.2 2307.23   438.6 2308.92   486.5 2311.22   542.8 2313.36     560 2314.18
   581.6  2315.9     602 2317.97   611.3 2319.52   643.9  2328.4657.9825 2332.64
#Mann= 3 ,-1 , 0
       0      .1       0   230.4    .045       0   241.7      .1       0
Bank Sta=230.4,241.7
XS Rating Curve= 0 ,0
Exp/Cntr(USF)=0,0
Exp/Cntr=0.3,0.1

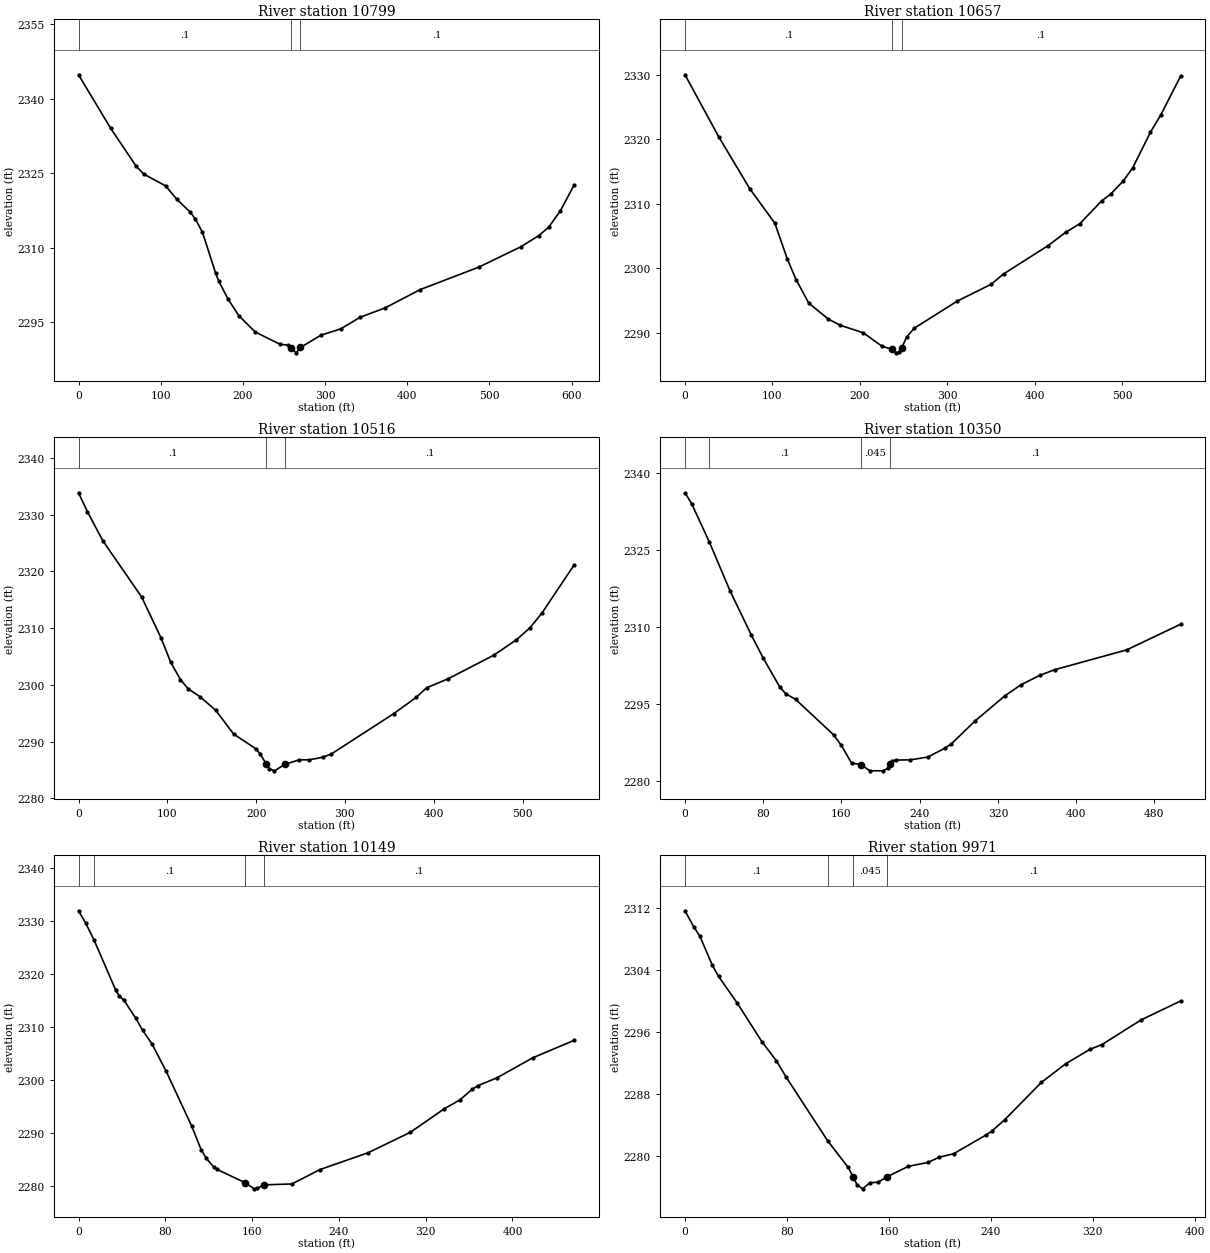
Type RM Length L Ch R = 1 ,10799   ,140.3,142.2,140.3
XS GIS Cut Line= 4
2492029.29864367 658305.374516252491891.25322637658416.779589861
2491796.80109875658542.7157600292491590.94389751658714.667069297
#Sta/Elev= 30
       0 2344.85    39.3 2334.02    70.1 2326.42    79.7  2324.8   106.1 2322.44
   119.5 2319.76   136.2 2317.11   142.3 2315.71   150.8  2313.1   166.7 2304.91
   170.7 2303.22   182.1 2299.57     195 2296.29     215 2292.99   245.4  2290.5
     255 2290.36   258.2 2289.81   264.9 2288.79     270 2289.87     295 2292.35
   319.3 2293.64   342.7 2295.97   372.5 2297.81   415.9 2301.55   486.9 2306.06
     538 2310.16   559.7 2312.39     572 2314.11   586.3 2317.44 603.036 2322.65
#Mann= 3 ,-1 , 0
       0      .1       0   258.2    .045       0     270      .1       0
Bank Sta=258.2,270
XS Rating Curve= 0 ,0
Exp/Cntr(USF)=0,0
Exp/Cntr=0.3,0.1

Type RM Length L Ch R = 1 ,10657   ,139.6,140.8,136.2
XS GIS Cut Line= 4
2491915.47172064658269.0467748562491791.95739989658353.811504776
2491658.75568145658467.6384278132491467.42957677658615.371242818
#Sta/Elev= 30
       0 2329.99    38.6 2320.38      74 2312.35   102.8 2306.98   116.9 2301.48
     127 2298.26   141.6 2294.59   163.8 2292.14   177.7 2291.17     204    2290
   225.3 2287.92   236.5 2287.45   240.8  2286.9   245.1 2287.01   247.9 2287.69
   253.6 2289.38   262.3 2290.73   311.5 2294.93     350 2297.52   364.4 2299.14
   415.4 2303.53   435.1 2305.56   451.4  2306.9   476.6 2310.47     487 2311.53
   501.3 2313.56     512 2315.58   532.2 2321.08   544.1 2323.78566.7391 2329.79
#Mann= 3 ,-1 , 0
       0      .1       0   236.5    .045       0   247.9      .1       0
Bank Sta=236.5,247.9
XS Rating Curve= 0 ,0
Exp/Cntr(USF)=0,0
Exp/Cntr=0.3,0.1

Type RM Length L Ch R = 1 ,10516   ,163.9,166.3,166.3
XS GIS Cut Line= 4
2491871.87843096658191.5475932142491733.83301366658252.093828872
2491588.52204808658361.0770530562491411.72703996658501.544319781
#Sta/Elev= 30
       0 2333.87      10 2330.55    27.4 2325.41    71.1  2315.5      93 2308.27
   103.6 2304.07   114.8 2300.95   123.5 2299.31   136.6 2297.95   154.6 2295.52
   174.6 2291.35   199.6 2288.76   204.6 2287.84  211.522286.027   214.9 2285.24
   220.7 2284.86   232.62286.028   248.7 2286.81   259.6 2286.79   274.9 2287.25
   284.6 2287.82   354.9 2294.93   380.5 2297.84   391.9 2299.49   416.4  2301.1
   467.5 2305.23     493 2307.94   508.6  2310.1   521.8 2312.65558.1824 2321.16
#Mann= 3 ,-1 , 0
       0      .1       0  211.52    .045       0   232.6      .1       0
Bank Sta=211.52,232.6
XS Rating Curve= 0 ,0
Exp/Cntr(USF)=0,0
Exp/Cntr=0.3,0.1

Type RM Length L Ch R = 1 ,10350   ,199.4,200.5,199.8
XS GIS Cut Line= 4
2491765.02713661658076.2414529852491643.40185842658129.207299938
2491511.96809005658205.7135233152491337.37696491658343.032385787
#Sta/Elev= 30
       0 2336.23     6.8 2334.12   24.812326.687    46.3 2317.03    67.9  2308.5
    79.7 2304.14    96.8 2298.45   102.8 2297.12   113.2 2295.98     152 2289.08
   159.9 2287.03   170.4 2283.57   179.7  2283.3     189 2282.09   202.8 2282.07
   207.5 2282.59  209.872283.333   212.1 2283.99   215.5 2284.17   230.6 2284.21
   248.5 2284.77     266  2286.5   272.3 2287.31   296.5 2291.76     327 2296.66
   343.4 2298.81   362.6 2300.65   377.9 2301.76   451.7 2305.63506.8596 2310.63
#Mann= 4 ,-1 , 0
       0      .1       0   24.81      .1       0   179.7    .045       0
  209.87      .1       0
Bank Sta=179.7,209.87
XS Rating Curve= 0 ,0
Exp/Cntr(USF)=0,0
Exp/Cntr=0.3,0.1

Type RM Length L Ch R = 1 ,10149   ,178.6,178.8,176.9
XS GIS Cut Line= 4
2491629.66997217657925.1907042662491545.31695665657958.539570866
2491368.76413348658076.2414529852491260.87074153658186.096542962
#Sta/Elev= 30
       0 2331.95     6.6 2329.62   14.252326.463    34.4 2316.92    37.5 2315.89
    41.9 2315.07    52.9 2311.62    59.1 2309.38    67.7 2306.83    80.6 2301.74
   104.4 2291.28   113.1 2286.83   117.8 2285.22   124.5 2283.63   127.4 2283.16
  153.442280.644     162 2279.47   164.9 2279.57   170.7 2280.22   196.7 2280.39
   222.6 2283.11   266.9 2286.28   305.8 2290.13   337.3  2294.6   351.5 2296.25
   362.8 2298.25   368.3 2298.96   385.7 2300.42   418.7  2304.2456.8737  2307.5
#Mann= 4 ,-1 , 0
       0      .1       0   14.25      .1       0  153.44    .045       0
   170.7      .1       0
Bank Sta=153.44,170.7
XS Rating Curve= 0 ,0
Exp/Cntr(USF)=0,0
Exp/Cntr=0.3,0.1

Type RM Length L Ch R = 1 ,9971    ,134.3,133.9,130.9
XS GIS Cut Line= 4
 2491492.3511097657778.0633516172491421.72998043  657827.1058025
2491288.33451403657929.1141003362491215.75168672658042.892586384
#Sta/Elev= 30
       0 2311.67     6.8 2309.62    11.7 2308.38    21.4 2304.66    26.3 2303.21
    40.9 2299.77    60.4 2294.75    71.6 2292.32    79.3  2290.2  112.062281.926
   127.9 2278.55  131.992277.285   135.1 2276.25   139.3 2275.75   145.1 2276.54
   151.5  2276.6  158.232277.283   175.3 2278.66   190.7 2279.16   199.2 2279.82
   210.7 2280.28   235.8 2282.67   240.8 2283.21   250.9 2284.69   279.7 2289.51
   298.7 2291.91   317.7 2293.77   327.2 2294.39   357.7 2297.56388.8669 2300.02
#Mann= 4 ,-1 , 0
       0      .1       0  112.06      .1       0  131.99    .045       0
  158.23      .1       0
Bank Sta=131.99,158.23
XS Rating Curve= 0 ,0
Exp/Cntr(USF)=0,0
Exp/Cntr=0.3,0.1

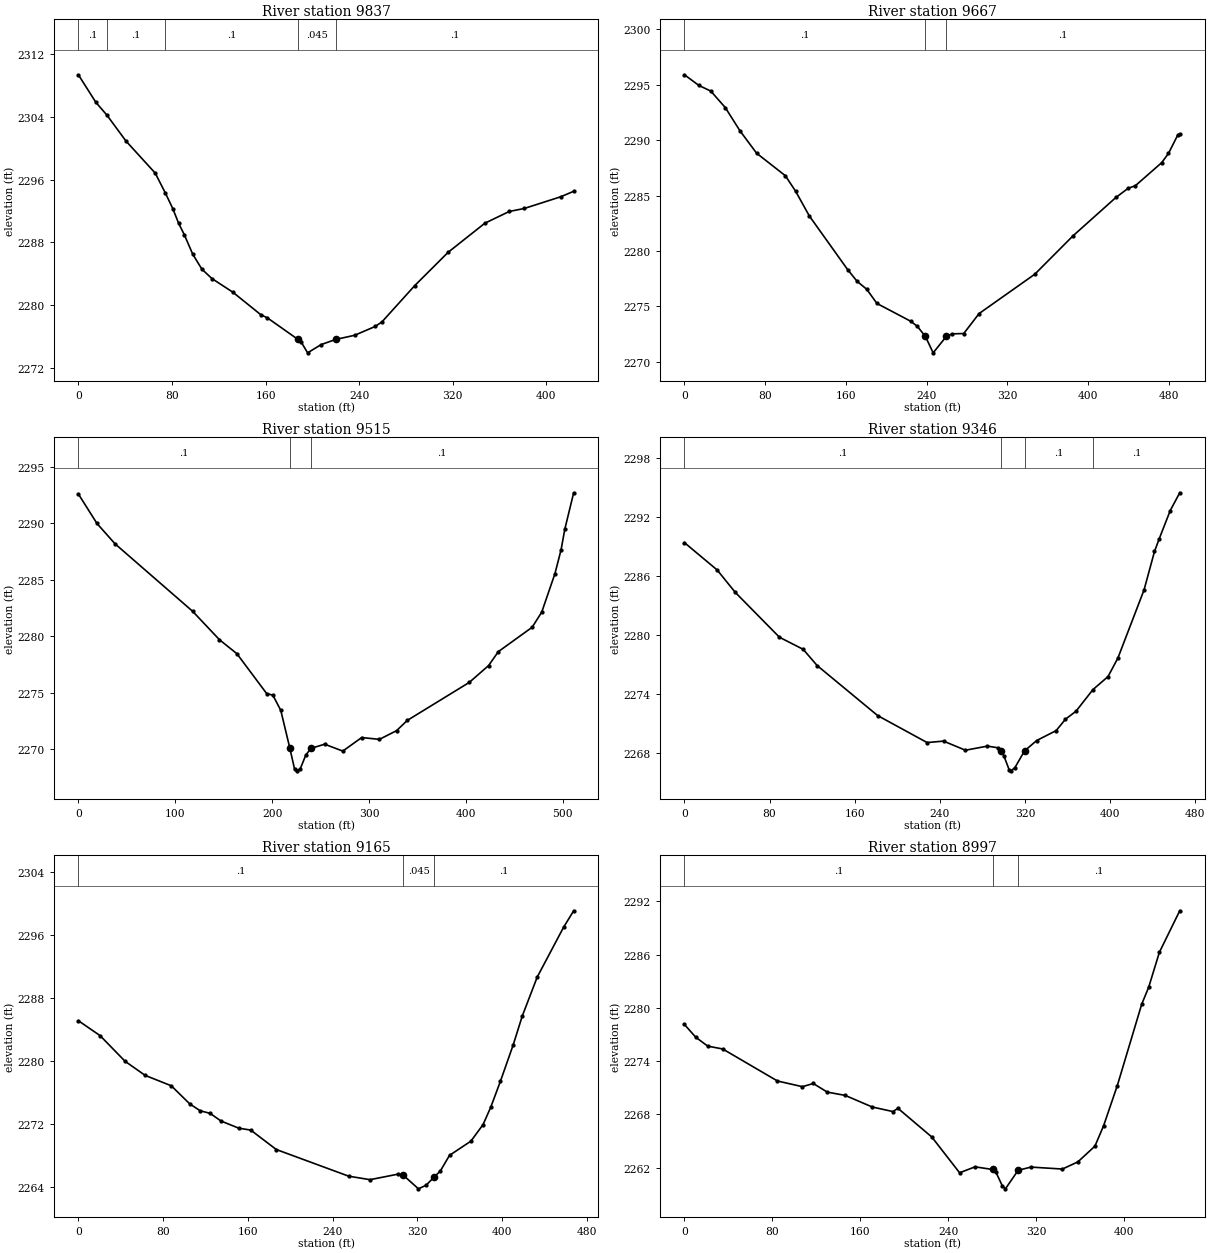
Type RM Length L Ch R = 1 ,9837    ,169.5,169.7,163.8
XS GIS Cut Line= 4
2491435.46186668657642.7061871812491335.41526688657717.250712523
2491202.01980048657846.7227828532491129.43697317657933.037496407
#Sta/Elev= 30
       0 2309.38    14.9 2305.88   24.442304.225    40.7 2300.93    65.7 2296.84
   74.452294.281    80.7 2292.32    85.7 2290.45    90.7 2288.94    97.8 2286.49
   105.6 2284.59   114.1  2283.4   132.1 2281.65   155.8  2278.8   161.6 2278.38
  187.792275.625   190.3 2275.34     196 2273.92   207.5 2274.97  219.942275.625
   236.2 2276.16   253.7 2277.28   259.5 2277.86   287.6  2282.5   316.1 2286.74
   347.5 2290.45   368.4 2291.95   381.2 2292.33   412.5 2293.83 423.437 2294.52
#Mann= 5 ,-1 , 0
       0      .1       0   24.44      .1       0   74.45      .1       0
  187.79    .045       0  219.94      .1       0
Bank Sta=187.79,219.94
XS Rating Curve= 0 ,0
Exp/Cntr(USF)=0,0
Exp/Cntr=0.3,0.1

Type RM Length L Ch R = 1 ,9667    ,151.6,152.4,153.3
XS GIS Cut Line= 4
2491355.03224723657515.195814886 2491198.0964044657615.242414687
2491103.93489871657736.8676928762491023.50527926657864.378065171
#Sta/Elev= 30
       0 2295.88    14.3 2294.92    26.1 2294.41    40.5 2292.92      55 2290.83
    71.5 2288.81     100 2286.78   110.1 2285.39   123.7 2283.16   161.6 2278.33
   171.1 2277.26   180.6 2276.55   190.7 2275.27   224.3 2273.66   230.8  2273.2
  238.732272.295   246.4 2270.82  259.422272.295   265.2 2272.53   276.7 2272.56
   291.9 2274.36     347  2277.9   384.9 2281.36   427.4 2284.82   439.6 2285.65
   446.7 2285.88   472.8 2287.96   479.5 2288.79   488.9 2290.48 490.686 2290.53
#Mann= 3 ,-1 , 0
       0      .1       0  238.73    .045       0  259.42      .1       0
Bank Sta=238.73,259.42
XS Rating Curve= 0 ,0
Exp/Cntr(USF)=0,0
Exp/Cntr=0.3,0.1

Type RM Length L Ch R = 1 ,9515    ,167.7,169,165.4
XS GIS Cut Line= 4
2491262.83243957657375.9152543792491121.59018103657503.425626674
2491017.62018516657611.3190186162490880.30132268657713.327316452
#Sta/Elev= 30
       0  2292.6    19.2 2289.99    37.8 2288.19   117.9 2282.21   145.6 2279.69
   163.6 2278.45   194.4 2274.91   200.7 2274.78   208.9 2273.43  218.152270.116
   223.2  2268.2   225.9 2268.07     229 2268.25   234.7 2269.46     240 2270.06
   254.2 2270.43   272.9 2269.82   292.4 2271.02   310.7 2270.86   328.4 2271.63
   339.5 2272.54   403.5 2275.91   423.4  2277.4   433.4 2278.63   468.3 2280.79
   478.2 2282.13   491.8 2285.53   498.2 2287.66     502 2289.47511.1823 2292.71
#Mann= 3 ,-1 , 0
       0      .1       0  218.15    .045       0     240      .1       0
Bank Sta=218.15,240
XS Rating Curve= 0 ,0
Exp/Cntr(USF)=0,0
Exp/Cntr=0.3,0.1

Type RM Length L Ch R = 1 ,9346    ,173.7,180.6,181.6
XS GIS Cut Line= 4
2491156.90074566657273.9069565432491037.23716551657368.068462237
2490909.72679321657525.0043050622490819.48868359657589.740340228
#Sta/Elev= 30
       0  2289.4    30.7 2286.62    47.8 2284.33    89.3 2279.76   111.6 2278.53
   124.7 2276.88   181.6 2271.78   228.1 2269.03   243.5 2269.18   264.1 2268.25
   284.8 2268.67   295.1 2268.49  297.31 2268.19   300.2 2267.69   305.4  2266.2
   306.8 2266.15   310.5 2266.46   319.72268.189   331.1 2269.24   349.4 2270.25
   358.1 2271.41     368 2272.22  383.992274.432   398.1 2275.75   407.4 2277.64
     432 2284.59   441.8  2288.5   446.3 2289.81   456.6 2292.67 465.533 2294.48
#Mann= 4 ,-1 , 0
       0      .1       0  297.31    .045       0   319.7      .1       0
  383.99      .1       0
Bank Sta=297.31,319.7
XS Rating Curve= 0 ,0
Exp/Cntr(USF)=0,0
Exp/Cntr=0.3,0.1

Type RM Length L Ch R = 1 ,9165    ,167.1,168,167.8
XS GIS Cut Line= 4
2491096.08810657657199.3624312012490980.34792249657271.945258507
2490770.44623271 657413.187517052490711.59529165657464.191665968
#Sta/Elev= 30
       0 2285.12    20.5 2283.23    44.1 2279.98      63  2278.2    87.7 2276.88
   105.1 2274.59   114.9 2273.72   124.3 2273.39   134.6 2272.42   151.4 2271.51
   162.7 2271.27   186.8 2268.81   255.2 2265.43   275.3 2264.99   301.3 2265.68
   306.7 2265.55     321 2263.83   328.2 2264.29  335.742265.314   341.6 2266.08
   350.3 2268.07   370.5 2269.87     382 2271.97   389.3 2274.19   398.3 2277.43
   410.4 2282.05     419 2285.72   433.1 2290.65     458 2296.96467.4919 2299.04
#Mann= 3 ,-1 , 0
       0      .1       0   306.7    .045       0  335.74      .1       0
Bank Sta=306.7,335.74
XS Rating Curve= 0 ,0
Exp/Cntr(USF)=0,0
Exp/Cntr=0.3,0.1

Type RM Length L Ch R = 1 ,8997    ,182.7,193.6,196.7
XS GIS Cut Line= 4
 2491025.4669773657079.6988510472490878.33962465657158.166772459
2490678.24642505657279.7920506482490640.97416238657313.140917249
#Sta/Elev= 30
       0 2278.14    10.3  2276.7    21.2  2275.7    34.8 2275.38    84.7 2271.77
   107.4 2271.13   117.3 2271.49     130 2270.52   146.3 2270.15     171 2268.84
   189.7 2268.33   194.4 2268.69   225.2 2265.46   250.5 2261.43   264.6  2262.1
   280.5  2261.8   283.3 2261.57   289.3 2259.98   292.2 2259.62   303.8 2261.71
   315.5 2262.07   344.1 2261.85   358.2 2262.66   373.7 2264.43   381.6 2266.73
   394.1 2271.26   416.3 2280.43   422.6 2282.32   432.4 2286.28450.9161 2290.95
#Mann= 3 ,-1 , 0
       0      .1       0   280.5    .045       0   303.8      .1       0
Bank Sta=280.5,303.8
XS Rating Curve= 0 ,0
Exp/Cntr(USF)=0,0
Exp/Cntr=0.3,0.1