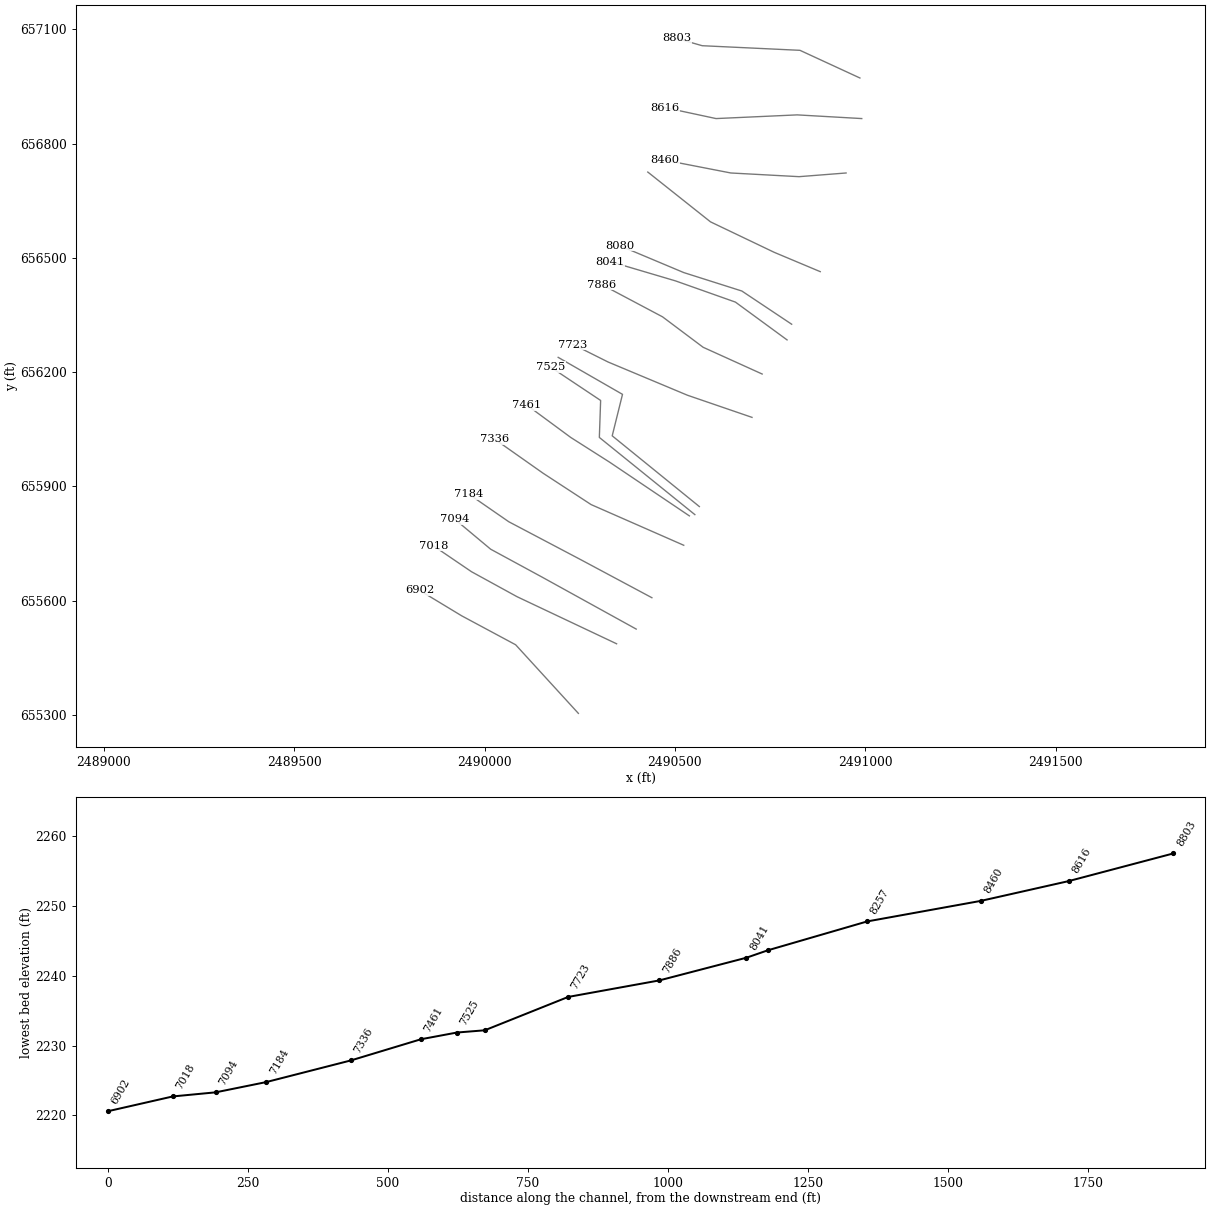
HEC-RAS study SHAVERN.prj: SHAVERN

--- SHAVERN.g01 (geometry) --- (continued)

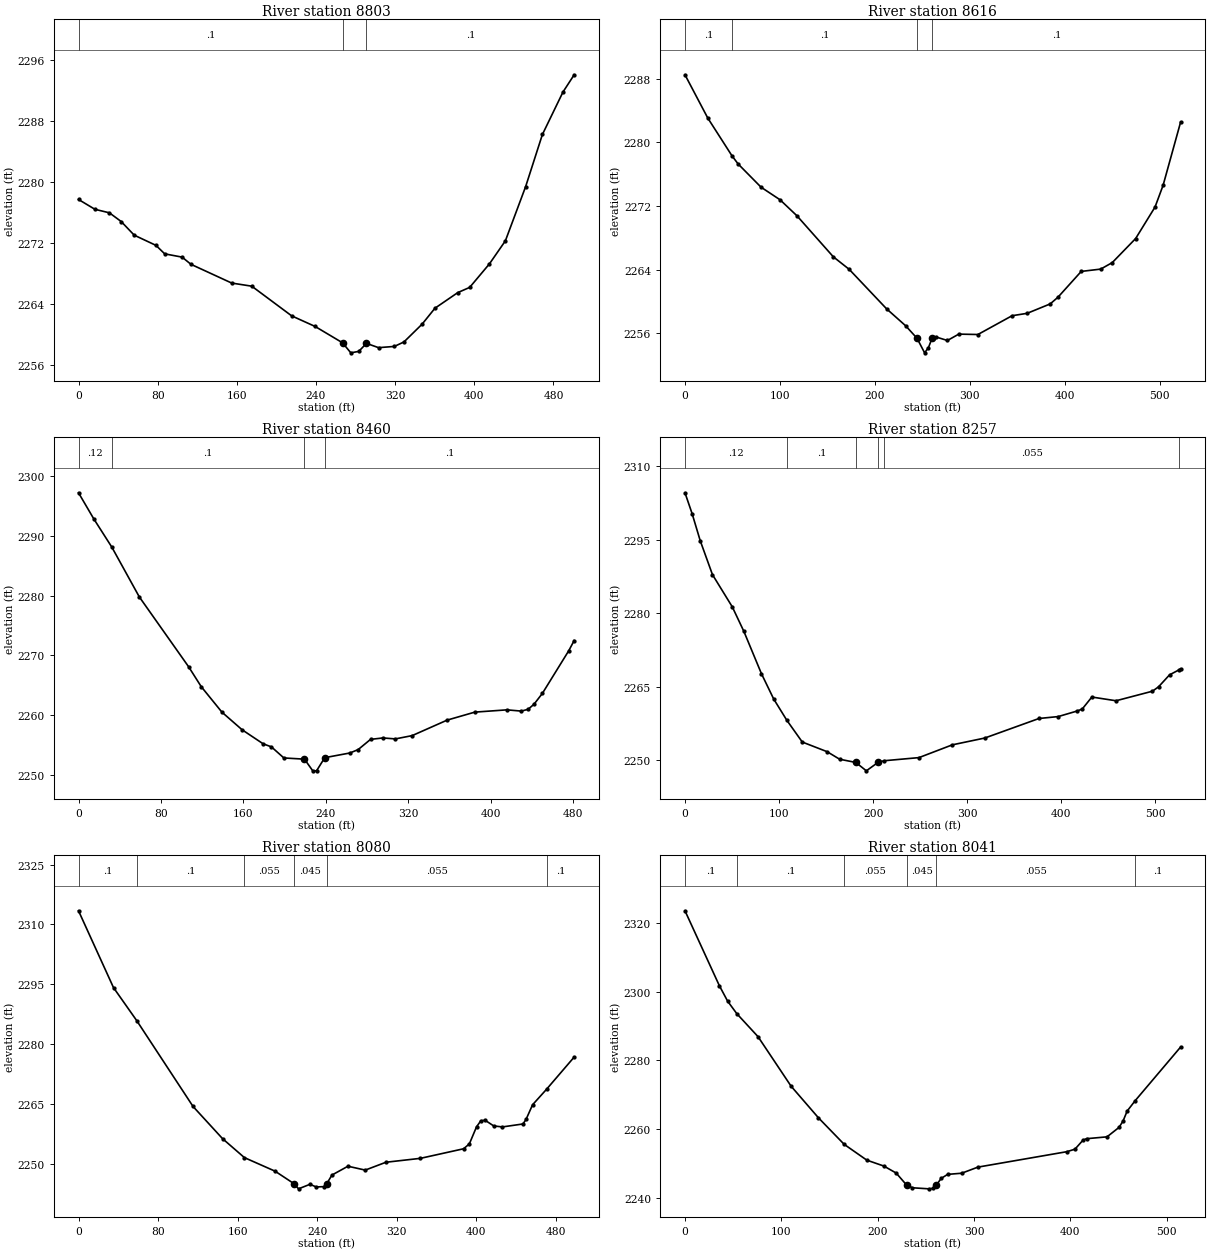
Type RM Length L Ch R = 1 ,8803    ,183.5,187.1,187.2
XS GIS Cut Line= 4
2490985.84552068656972.5320139332490828.42530797657045.187496722
2490571.70926878657057.2967438532490503.89748485657076.671539264
#Sta/Elev= 30
       0 2277.65    16.6 2276.36    31.2  2275.9    43.1 2274.76    56.3 2272.97
    78.3 2271.63    87.1 2270.52   104.7 2270.09   113.6 2269.15   154.8 2266.69
   175.1 2266.28   215.4 2262.39   239.1    2261  266.822258.858   275.2 2257.54
   283.2 2257.73     291 2258.78   303.2 2258.22   319.2 2258.38   328.9 2258.97
   347.3 2261.31   360.2 2263.39   383.3 2265.44   395.3 2266.12   415.3 2269.21
   431.4 2272.23   451.9 2279.35   468.8 2286.17   489.6 2291.74500.9048    2294
#Mann= 3 ,-1 , 0
       0      .1       0  266.82    .045       0     291      .1       0
Bank Sta=266.82,291
XS Rating Curve= 0 ,0
Exp/Cntr(USF)=0,0
Exp/Cntr=0.3,0.1

Type RM Length L Ch R = 1 ,8616    ,157.1,156.4,155.7
XS GIS Cut Line= 4
2490990.68921954656865.9706391752490821.15975969 656875.65803688
2490608.03701018656865.9706391752490472.41344231656895.032832291
#Sta/Elev= 30
       0 2288.47      24 2283.04   49.522278.294      56 2277.27    80.1 2274.36
   100.1 2272.78   117.9 2270.77   156.2 2265.62   172.9 2264.05   212.3 2259.09
   232.3 2256.97   244.3  2255.4   252.3 2253.57   256.3 2254.22   260.3 2255.44
   264.3 2255.56   276.3 2255.12   288.3 2255.92   308.4 2255.87   344.4 2258.23
   360.3 2258.53   384.5 2259.71   392.7 2260.55   417.2 2263.79   437.7 2264.08
   449.9  2264.9   474.5 2267.92   494.9 2271.87   503.4  2274.6521.8513 2282.54
#Mann= 4 ,-1 , 0
       0      .1       0   49.52      .1       0   244.3    .045       0
   260.3      .1       0
Bank Sta=244.3,260.3
XS Rating Curve= 0 ,0
Exp/Cntr(USF)=0,0
Exp/Cntr=0.3,0.1

Type RM Length L Ch R = 1 ,8460    ,205.2,203.2,194.8
XS GIS Cut Line= 4
2490949.51777929656723.0815230232490826.00345855656713.394125317
  2490646.786601656723.0815230232490472.41344231656756.987414991
#Sta/Elev= 30
       0 2297.15    14.8  2292.8    32.42288.059      59 2279.77   106.9  2268.1
   119.1 2264.79   139.2 2260.53   158.8 2257.59   179.2 2255.25   187.2 2254.74
   199.3 2252.89   219.3 2252.69   227.3 2250.75     231 2250.74  238.972252.937
   263.4 2253.72   271.4 2254.29   283.4 2255.99   295.4 2256.23   307.5 2256.07
   323.8 2256.62   357.8 2259.21   384.6 2260.54   415.8 2260.92   429.7 2260.71
   436.3 2261.01     442 2261.85   450.1 2263.65   475.7 2270.77481.0111 2272.49
#Mann= 4 ,-1 , 0
       0     .12       0    32.4      .1       0   219.3    .045       0
  238.97      .1       0
Bank Sta=219.3,238.97
XS Rating Curve= 0 ,0
Exp/Cntr(USF)=0,0
Exp/Cntr=0.3,0.1

Type RM Length L Ch R = 1 ,8257    ,181.7,177,166.5
XS GIS Cut Line= 4
2490881.70599535656463.9436344082490760.61352404 656514.80247236
2490593.50591362656594.7235034282490428.82015263656725.503372449
#Sta/Elev= 30
       0 2304.57     7.6  2300.3    16.2 2294.79    29.2 2287.86    50.3 2281.27
    62.6 2276.27    81.3 2267.62    94.3 2262.46  108.352258.091   124.7 2253.67
   151.1  2251.7   164.4 2250.16  181.632249.503   192.8 2247.79  205.112249.502
  211.552249.849   248.7 2250.49   284.2  2253.1   318.7 2254.49   376.3 2258.48
   396.7 2258.87   417.1 2260.02   422.3 2260.42   432.5 2262.86   458.2  2262.1
   496.9 2264.05   503.4 2264.95   515.1 2267.39  525.462268.441 526.872  2268.6
#Mann= 6 ,-1 , 0
       0     .12       0  108.35      .1       0  181.63    .045       0
  205.11      .1       0  211.55    .055       0  525.46      .1       0
Bank Sta=181.63,205.11
XS Rating Curve= 0 ,0
Exp/Cntr(USF)=0,0
Exp/Cntr=0.3,0.1

Type RM Length L Ch R = 1 ,8080    ,34.7,38.5,41
XS GIS Cut Line= 4
2490806.62866314656325.8982171082490675.84879412656413.084796455
2490523.27228026656461.5217849812490356.16466984656531.755418344
#Sta/Elev= 30
       0 2313.41    35.2 2294.13   58.572285.847   115.2 2264.32   144.9 2256.24
  166.852251.494   197.7 2248.09  217.042244.902   221.3 2243.66   232.8  2244.8
   239.1 2244.13   246.5 2244.21  249.592244.904   254.9 2247.12     271 2249.33
   288.4 2248.36   309.2 2250.33   343.9 2251.31   387.3 2253.71   393.1 2254.93
   400.3  2259.2   404.6 2260.72   408.9 2260.87   417.6 2259.44   426.3 2259.19
     447 2259.93   450.1 2261.06   456.7 2264.75  470.712268.629498.5252 2276.71
#Mann= 6 ,-1 , 0
       0      .1       0   58.57      .1       0  166.85    .055       0
  217.04    .045       0  249.59    .055       0  470.71      .1       0
Bank Sta=217.04,249.59
XS Rating Curve= 0 ,0
Exp/Cntr(USF)=0,0
Exp/Cntr=0.3,0.1

Type RM Length L Ch R = 1 ,8041    ,160.4,155.3,141.9
XS GIS Cut Line= 4
  2490794.519416656284.7267768612490658.89584813656384.022603339
2490501.47563542656439.7251401442490329.52432615656490.583978097
#Sta/Elev= 30
       0  2323.5    35.7 2301.69    44.3 2297.18    53.82293.557    75.8 2286.87
   110.1 2272.47   138.5 2263.26  165.272255.525   188.7 2250.94   206.4 2249.22
   219.2 2247.18  229.932243.718   236.1  2242.9   253.1 2242.59   257.4  2242.7
  261.012243.717   265.8 2245.61   272.6  2246.8   287.1 2247.13     304 2248.91
   396.3  2253.4   404.7 2254.13     413 2256.73   416.7 2257.18     438 2257.72
   450.5 2260.48   454.7 2262.37   458.9 2265.23  467.262268.259514.3873 2283.86
#Mann= 6 ,-1 , 0
       0      .1       0    53.8      .1       0  165.27    .055       0
  229.93    .045       0  261.01    .055       0  467.26      .1       0
Bank Sta=229.93,261.01
XS Rating Curve= 0 ,0
Exp/Cntr(USF)=0,0
Exp/Cntr=0.3,0.1

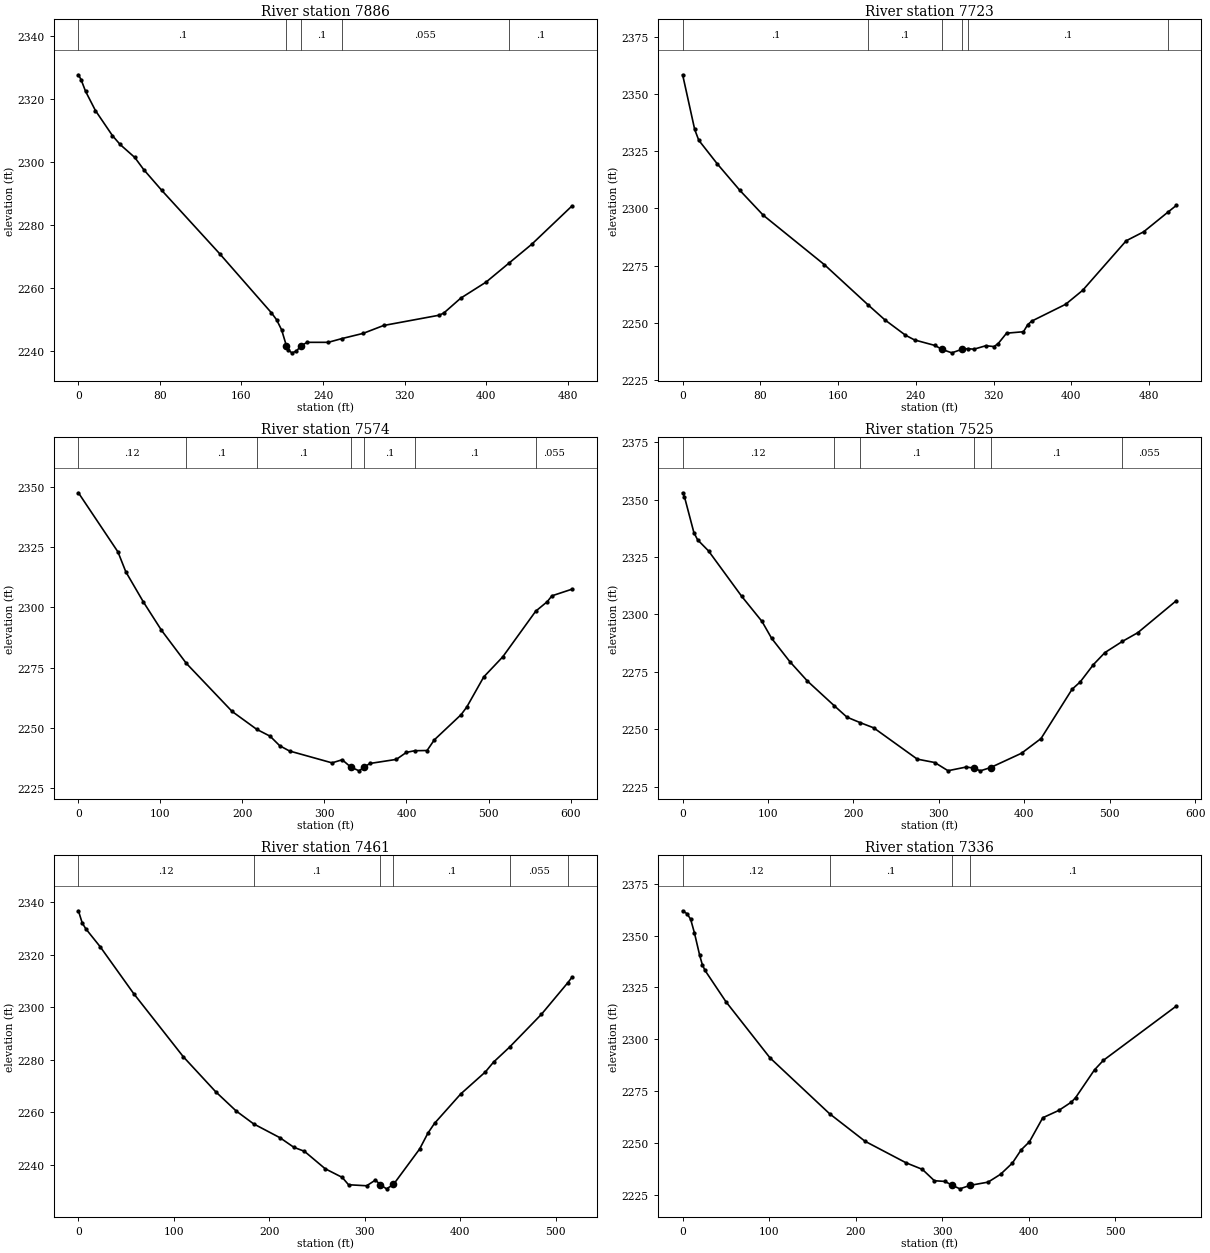
Type RM Length L Ch R = 1 ,7886    ,158.7,162.8,164.6
XS GIS Cut Line= 4
2490729.12948149656195.1183480872490574.13111821 656265.35198145
2490467.56974345656345.2730125182490307.72768132656430.037742439
#Sta/Elev= 30
       0 2327.72     2.6 2326.18       7 2322.48    16.7 2316.35    33.4 2308.38
    40.9 2305.57    55.3 2301.44    64.1 2297.57    81.7 2291.01   138.8 2270.77
   189.4 2252.05   194.4 2249.88   199.4 2246.62  204.052241.593   206.1 2240.21
   209.4 2239.34   213.7 2239.85  218.472241.587   224.4 2242.68   245.1 2242.68
  258.572243.877   279.4 2245.53   299.4 2248.03   354.1 2251.31   358.6 2252.02
   375.1 2256.72   399.9 2261.81  422.452267.864   444.7 2273.83484.2969 2286.04
#Mann= 5 ,-1 , 0
       0      .1       0  204.05    .045       0  218.47      .1       0
  258.57    .055       0  422.45      .1       0
Bank Sta=204.05,218.47
XS Rating Curve= 0 ,0
Exp/Cntr(USF)=0,0
Exp/Cntr=0.3,0.1

Type RM Length L Ch R = 1 ,7723    ,163.1,148.9,137.6
XS GIS Cut Line= 4
2490702.48913781656081.2914250512490532.95967796656139.415811282
 2490324.6806273656226.602390629 2490232.6503491656272.617529729
#Sta/Elev= 30
       0 2358.31    12.4 2334.44    16.6 2329.74    35.7 2319.41    58.9 2307.86
    82.9 2297.04   145.9 2275.43  191.182257.764     208 2251.39   229.3 2244.66
   238.6  2242.6   259.7 2240.18  266.722238.498     277 2236.97  287.192238.499
  293.322238.791   299.7 2238.56   311.9 2240.06   320.4 2239.71   324.7 2241.03
   333.3 2245.55   350.7 2246.18   355.1  2249.3   359.4 2250.86   394.1 2258.16
   411.6 2264.25   456.4 2285.88   474.3 2289.77  499.33 2298.37 507.901 2301.28
#Mann= 6 ,-1 , 0
       0      .1       0  191.18      .1       0  266.72    .045       0
  287.19      .1       0  293.32      .1       0  499.33    .055       0
Bank Sta=266.72,287.19
XS Rating Curve= 0 ,0
Exp/Cntr(USF)=0,0
Exp/Cntr=0.3,0.1

Type RM Length L Ch R = 1 ,7574    ,47.7,49.6,49.2
XS GIS Cut Line= 4
2490564.20208091655847.045222815 2490335.3570306656032.823492442
2490362.37932436656141.7571141772490193.48998834656238.868482392
#Sta/Elev= 30
       0  2347.6    48.2 2323.06    57.8  2314.8    79.2 2302.29   101.3 2290.52
  131.612276.789   187.4 2256.84  217.452249.408   233.7 2246.57   245.5 2242.59
   257.4 2240.42   309.2  2235.5   321.6 2236.79  331.992233.766   342.2 2232.19
  348.472233.768   355.4 2235.25   387.6 2236.94   399.9 2239.86  410.082240.538
   425.1 2240.63   433.9 2245.04   466.6 2255.52   473.5 2258.68   494.2 2271.18
   517.3 2279.48  557.532298.456   571.6  2302.4   577.3 2304.83601.8139 2307.59
#Mann= 7 ,-1 , 0
       0     .12       0  131.61      .1       0  217.45      .1       0
  331.99    .045       0  348.47      .1       0  410.08      .1       0
  557.53    .055       0
Bank Sta=331.99,348.47
XS Rating Curve= 0 ,0
Exp/Cntr(USF)=0,0
Exp/Cntr=0.3,0.1

Type RM Length L Ch R = 1 ,7525    ,55.3,64.1,75.1
XS GIS Cut Line= 4
2490552.37982739655825.9340558112490301.57916339656028.601259041
2490304.95695011656125.7126272552490173.22326802656213.535081988
#Sta/Elev= 30
       0 2352.94     2.1 2351.23    13.2 2335.57    17.5 2332.47    30.3 2327.63
      69 2307.93    92.9 2296.93   104.2 2289.56   125.5 2279.42   146.1 2270.96
  177.312260.287   192.4 2255.24  207.622252.897   223.7 2250.59   274.7 2236.97
   295.2 2235.49   310.7 2231.92   331.9 2233.52   340.8 2233.09   348.5 2231.87
  360.512233.298   396.8 2239.54   419.6 2245.93   455.9 2267.36   465.5 2270.59
     481 2278.15   494.4 2283.36  514.892288.233   532.9 2292.02577.9458 2305.93
#Mann= 6 ,-1 , 0
       0     .12       0  177.31      .1       0  207.62      .1       0
   340.8    .045       0  360.51      .1       0  514.89    .055       0
Bank Sta=340.8,360.51
XS Rating Curve= 0 ,0
Exp/Cntr(USF)=0,0
Exp/Cntr=0.3,0.1

Type RM Length L Ch R = 1 ,7461    ,125.6,124.8,123.4
XS GIS Cut Line= 4
2490538.02423383655822.5562690912490328.60145716655963.578864672
2490226.42340886656028.6012590412490110.73421369656113.890373733
#Sta/Elev= 30
       0 2336.69       4 2332.04     7.8 2329.81    22.8 2323.02    57.9  2305.2
     110 2281.13   143.8 2267.87   165.3 2260.54  183.51 2255.65   211.3 2250.34
   225.8 2246.71   236.9 2245.18   258.6 2238.56   276.5 2235.26   283.1 2232.47
   302.1 2232.08   311.3 2234.25   316.3 2232.51   322.9 2230.91  330.182232.572
   357.6 2246.07   366.3 2252.11   373.2 2255.82   400.7 2267.02   426.5 2275.38
   435.1 2279.13   451.92284.835   485.3 2297.33  513.04 2309.39517.3206 2311.44
#Mann= 6 ,-1 , 0
       0     .12       0  183.51      .1       0   316.3    .045       0
  330.18      .1       0   451.9    .055       0  513.04      .1       0
Bank Sta=316.3,330.18
XS Rating Curve= 0 ,0
Exp/Cntr(USF)=0,0
Exp/Cntr=0.3,0.1

Type RM Length L Ch R = 1 ,7336    ,149.4,151.4,151.4
XS GIS Cut Line= 4
2490523.21237392655745.4198424122490279.95612862655852.246659133
2490153.82326069655934.6191443152490027.69039275656023.426979901
#Sta/Elev= 30
       0 2361.99     4.9 2360.62     9.2 2357.98    13.6 2351.38    19.7  2340.5
    22.7 2336.07    25.8 2333.27      50 2318.16     101 2291.04  169.792264.127
   210.9 2250.81   258.3 2240.43   277.1 2237.27     291 2231.79   303.1 2231.46
  311.912229.547   320.5 2227.88  332.132229.548   353.1 2231.12   367.5 2234.91
   381.2 2240.33   391.3 2246.68   400.9  2250.6   416.3 2262.17   434.8  2265.7
   449.4 2269.72   454.3  2271.9   476.1 2285.29   486.3 2289.84570.5877 2316.01
#Mann= 4 ,-1 , 0
       0     .12       0  169.79      .1       0  311.91    .045       0
  332.13      .1       0
Bank Sta=311.91,332.13
XS Rating Curve= 0 ,0
Exp/Cntr(USF)=0,0
Exp/Cntr=0.3,0.1

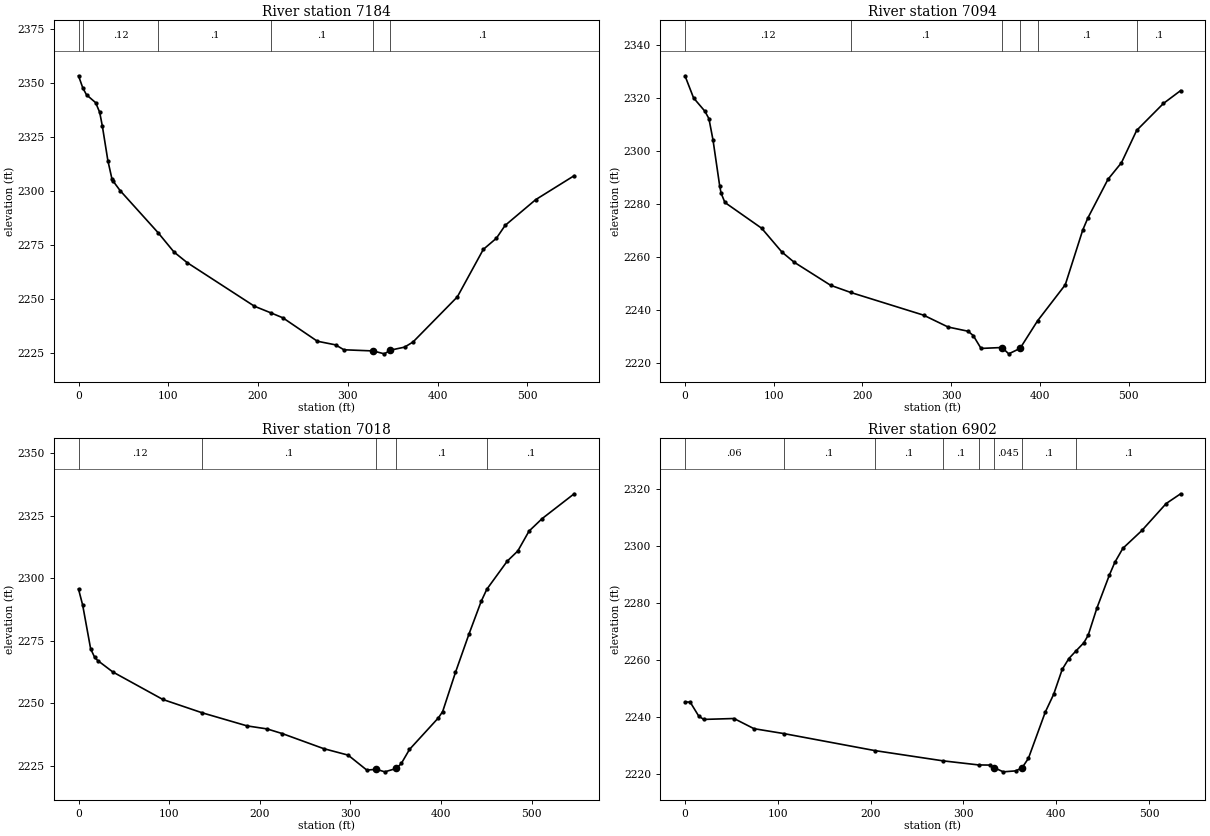
Type RM Length L Ch R = 1 ,7184    ,91.4,90.2,91.6
XS GIS Cut Line= 4
2490439.55281866655607.703343749  2490254.214727655706.807739983
2490063.72835502655807.1992062992489959.47567846655879.275130833
#Sta/Elev= 30
       0 2353.37    4.782347.748     8.9 2344.57    19.1 2340.93    23.6 2336.47
    26.6    2330    32.7 2314.16    37.2 2305.75    38.4 2304.74    46.3  2300.3
   88.652280.804   106.4 2271.85   120.9    2267     196 2246.79  214.752243.649
   227.7 2241.43   266.1  2230.6   286.4 2228.92   295.7 2226.65   328.3 2226.11
   340.7 2224.77   347.6 2226.48   363.3 2227.87   372.7 2230.25   422.1 2251.13
     451 2273.07   465.6 2278.24   475.3 2284.16   509.4 2296.09 552.235 2307.16
#Mann= 6 ,-1 , 0
       0      .1       0    4.78     .12       0   88.65      .1       0
  214.75      .1       0   328.3    .045       0   347.6      .1       0
Bank Sta=328.3,347.6
XS Rating Curve= 0 ,0
Exp/Cntr(USF)=0,0
Exp/Cntr=0.3,0.1

Type RM Length L Ch R = 1 ,7094    ,76.6,76.7,76.4
XS GIS Cut Line= 4
2490398.36657607655525.3308585672490151.24912052655661.760287149
2490016.10676202655735.1232817652489922.15064611655813.634556704
#Sta/Elev= 30
       0 2328.28     9.7 2319.91    22.4 2314.91      27 2312.08    31.6    2304
    39.1 2286.73    40.7 2283.95      45 2280.44    86.4 2270.72   109.2 2261.74
   122.9 2257.92   164.1 2249.18  186.592246.491   268.8 2237.91   296.5 2233.42
   318.9 2231.84   324.8 2230.21   333.6 2225.34   357.2 2225.69   364.8  2223.3
  377.562225.352  397.272235.758   428.5 2249.37   448.2 2270.05   453.9 2274.55
   476.6 2289.18   491.8 2295.45  508.962307.667   539.1 2317.83558.4886 2322.69
#Mann= 6 ,-1 , 0
       0     .12       0  186.59      .1       0   357.2    .045       0
  377.56      .1       0  397.27      .1       0  508.96      .1       0
Bank Sta=357.2,377.56
XS Rating Curve= 0 ,0
Exp/Cntr(USF)=0,0
Exp/Cntr=0.3,0.1

Type RM Length L Ch R = 1 ,7018    ,114.2,115.8,115
XS GIS Cut Line= 4
2490346.88377283655486.7187561382490085.60854639655610.277483911
2489965.91102886 655675.918058042489865.51956255655744.132772331
#Sta/Elev= 30
       0 2295.67     4.6 2289.25    13.4 2271.79    17.9 2268.36    21.3 2267.11
    37.8 2262.59    93.1 2251.59  136.392246.281     186 2241.05   208.1 2239.84
     225 2237.96   270.6 2231.96   297.5 2229.38   318.1 2223.41   328.8 2223.72
   337.9 2222.71  350.81 2224.08   356.2 2226.06   365.2 2231.65   397.2  2244.3
   401.8 2246.77   415.9 2262.37   430.8 2277.66   444.3 2290.75  450.512295.582
   473.1 2306.83   484.7 2310.86   497.1  2318.8   511.6  2323.8546.9067  2333.7
#Mann= 5 ,-1 , 0
       0     .12       0  136.39      .1       0   328.8    .045       0
  350.81      .1       0  450.51      .1       0
Bank Sta=328.8,350.81
XS Rating Curve= 0 ,0
Exp/Cntr(USF)=0,0
Exp/Cntr=0.3,0.1

Type RM Length L Ch R = 1 ,6902    ,139.9,137.9,137.8
XS GIS Cut Line= 4
2490246.49230651655303.9548046412490081.74733615655484.144615976
2489940.16962724655560.0817507532489829.48160028655627.009394963
#Sta/Elev= 30
       0 2245.15     5.6 2245.11    14.8  2240.2    20.2 2239.02    52.8 2239.34
    74.4 2235.76  106.232234.058  204.672228.058  277.992224.459  316.452223.018
   328.2 2222.97  333.292222.043     343 2220.59   356.5 2220.93  363.332222.042
   370.1 2225.32   388.3  2241.6   397.3 2247.83   406.5 2256.58   413.7 2260.42
  421.81 2263.25   429.8 2265.95   434.5 2268.59   443.9 2278.15   457.4  2289.8
   463.2 2294.22   471.9 2299.17   492.4 2305.44   518.6 2314.93534.1561 2318.35
#Mann= 8 ,-1 , 0
       0     .06       0  106.23      .1       0  204.67      .1       0
  277.99      .1       0  316.45      .1       0  333.29    .045       0
  363.33      .1       0  421.81      .1       0
Bank Sta=333.29,363.33
XS Rating Curve= 0 ,0
Exp/Cntr(USF)=0,0
Exp/Cntr=0.3,0.1