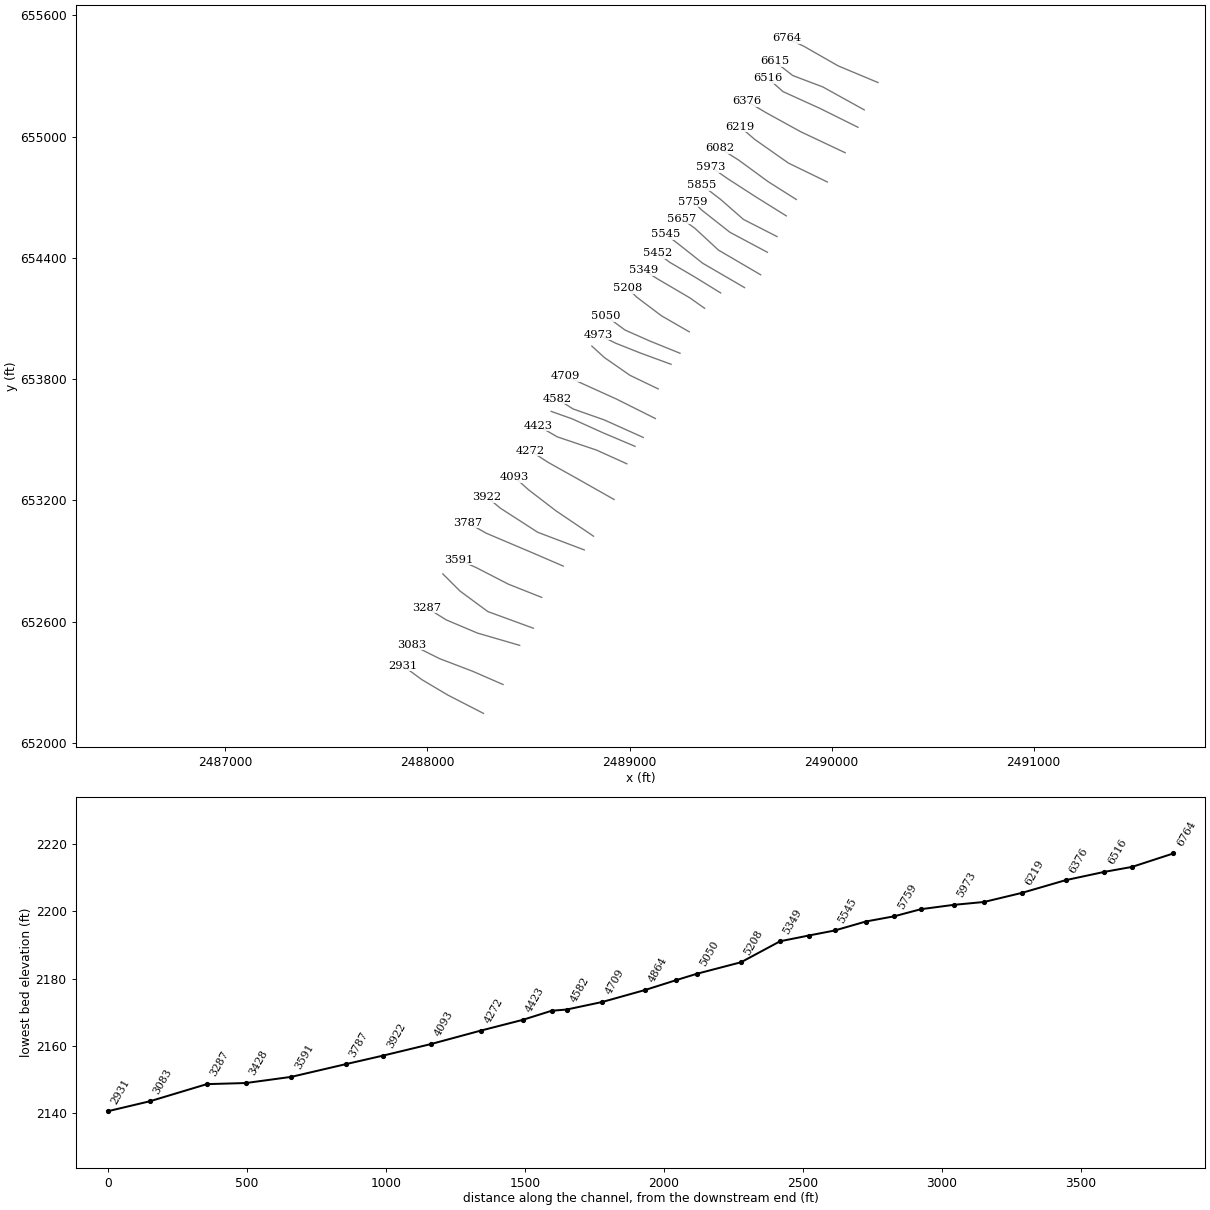
HEC-RAS study SHAVERN.prj: SHAVERN

--- SHAVERN.g01 (geometry) --- (continued)

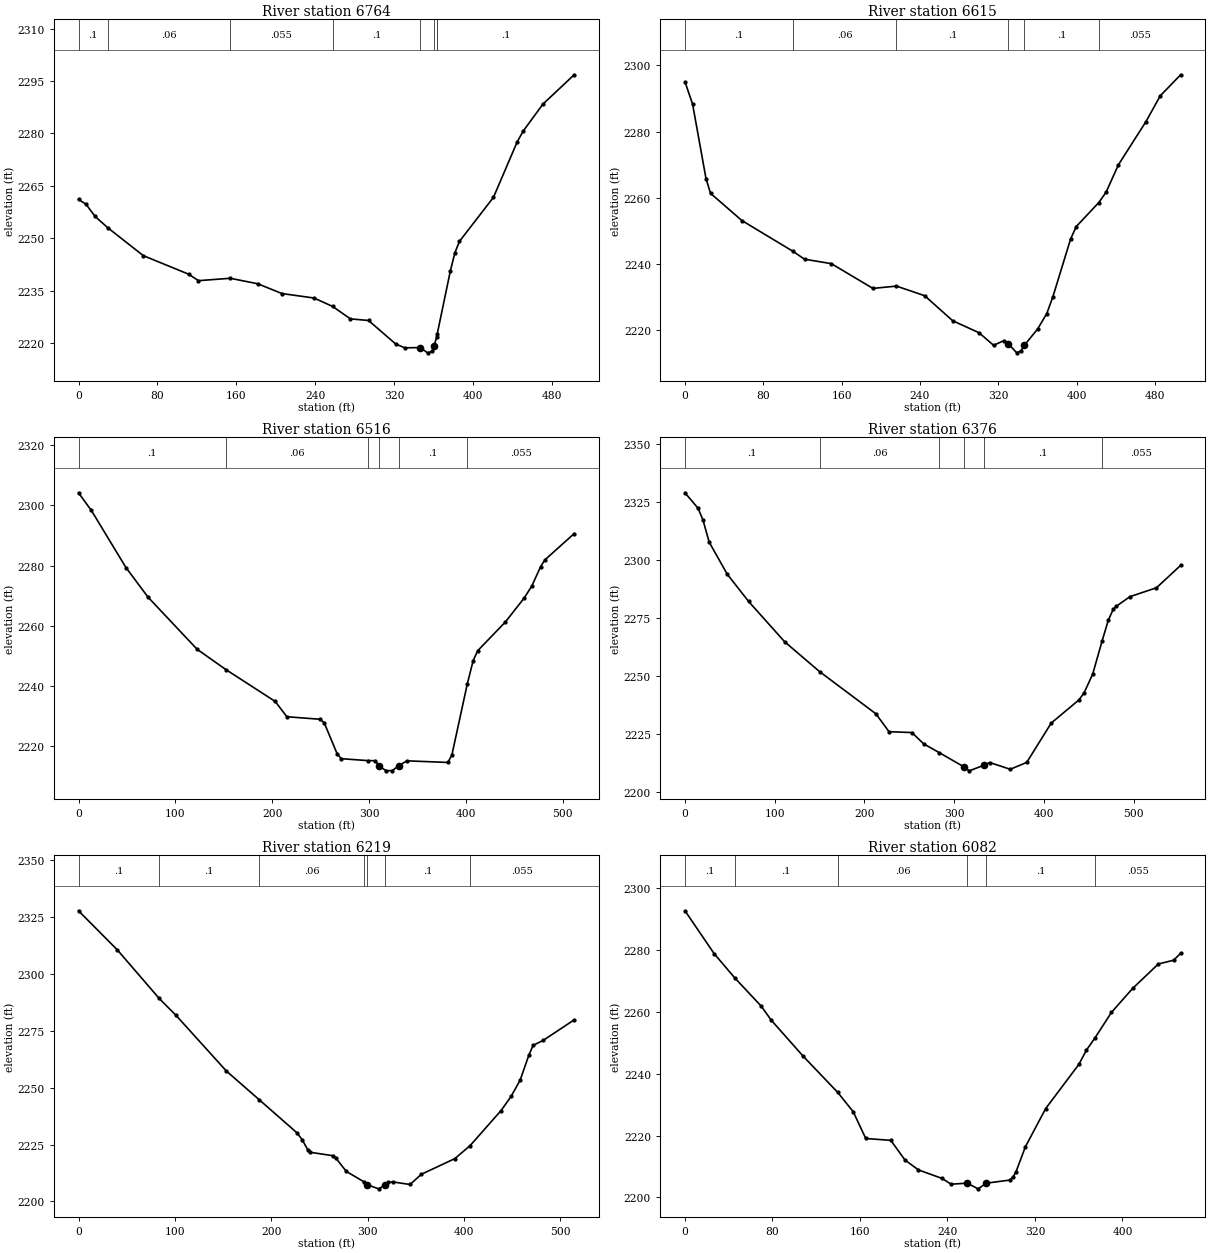
Type RM Length L Ch R = 1 ,6764    ,147.2,148.9,149.8
XS GIS Cut Line= 4
2490229.76039546655267.9168423732490032.83867307655350.289327555
2489861.65835231655448.1066537092489777.99879704655486.718756138
#Sta/Elev= 30
       0 2261.11     7.6 2259.76    16.8 2256.26   29.67 2253.03    65.7 2245.04
   111.6 2239.74   121.7 2237.88     1542238.558   181.9 2236.98   206.3 2234.19
   238.9 2232.91  257.772230.495   275.8 2226.94   294.2 2226.48   321.8 2219.73
     331 2218.65   346.5 2218.73   354.1 2217.22   358.7 2217.62  360.722219.238
  363.212221.693  363.832222.588   377.1 2240.58   381.7 2245.78   386.3 2249.09
   420.9 2261.72     445 2277.62   451.1 2280.71   471.1 2288.41502.7531  2296.8
#Mann= 8 ,-1 , 0
       0      .1       0   29.67     .06       0     154    .055       0
  257.77      .1       0   346.5    .045       0  360.72      .1       0
  363.21      .1       0  363.83      .1       0
Bank Sta=346.5,360.72
XS Rating Curve= 0 ,0
Exp/Cntr(USF)=0,0
Exp/Cntr=0.3,0.1

Type RM Length L Ch R = 1 ,6615    ,100.2,99.3,98
XS GIS Cut Line= 4
2490161.54568117655132.774483872 2489956.9015383655246.036650997
 2489807.6014089 655302.667734562489718.79357332655372.169518932
#Sta/Elev= 30
       0 2295.07     7.8  2288.3    21.5  2265.8    26.1 2261.39    58.1 2253.17
  110.552243.827   122.1 2241.49   149.5 2240.15     192 2232.67  216.072233.365
   244.8 2230.47   273.5  2222.9   300.4 2219.28   315.3 2215.48     326 2216.93
   330.3 2215.95   338.9 2213.21   343.2  2213.8  346.582215.441   360.3 2220.43
   369.6 2225.08   375.8  2230.1   393.9 2247.55   399.7 2251.35  422.592258.545
   430.2 2261.73   442.8 2270.01   470.9 2283.04   485.5 2290.82506.3473 2297.19
#Mann= 6 ,-1 , 0
       0      .1       0  110.55     .06       0  216.07      .1       0
   330.3    .045       0  346.58      .1       0  422.59    .055       0
Bank Sta=330.3,346.58
XS Rating Curve= 0 ,0
Exp/Cntr(USF)=0,0
Exp/Cntr=0.3,0.1

Type RM Length L Ch R = 1 ,6516    ,140.3,139.7,138.7
XS GIS Cut Line= 4
2490130.65599923655046.5407884472489944.03083749655139.209834277
2489759.97981591655222.8693895392489684.04268113 655289.79703375
#Sta/Elev= 30
       0 2304.19    13.3  2298.3      49 2279.32    71.8 2269.48   122.5 2252.14
  152.292245.381   203.1 2234.81   215.1 2229.73   249.3 2228.89   253.7 2227.71
   266.9  2217.5   271.3 2215.78  298.462215.147   306.4 2215.11  310.042213.414
   317.8 2211.74     324 2211.84  330.572213.413     339 2215.07   381.3 2214.53
   385.5 2217.01   401.42240.614   407.5 2248.42   412.2 2251.69   440.8 2261.25
   460.2 2269.22   468.1 2273.23   477.1 2279.62   481.5 2281.87  511.76 2290.62
#Mann= 6 ,-1 , 0
       0      .1       0  152.29     .06       0  298.46      .1       0
  310.04    .045       0  330.57      .1       0   401.4    .055       0
Bank Sta=310.04,330.57
XS Rating Curve= 0 ,0
Exp/Cntr(USF)=0,0
Exp/Cntr=0.3,0.1

Type RM Length L Ch R = 1 ,6376    ,157.7,156.5,156.2
XS GIS Cut Line= 4
2490067.20644563 654920.609190732489846.51541666655024.775356406
2489673.49364995655120.1138809222489578.15512543655176.610784339
#Sta/Elev= 30
       0 2328.89    14.7 2322.18    20.1  2317.1      27 2307.63    47.1 2293.86
    70.9 2282.15   111.1 2264.79  150.042251.952   212.8  2233.8   227.4 2226.11
   252.9 2225.74     266  2220.9  283.652217.041  310.782211.015   316.8 2209.27
   333.8 2211.77   339.7 2212.84   362.5 2209.94   380.9  2212.9   408.2 2229.83
   439.1 2239.79   444.8 2242.82   454.4 2250.87  464.762264.974   471.9 2274.21
   477.3 2278.76   480.7 2280.07   495.9  2284.2   525.5 2288.03552.4103 2297.65
#Mann= 6 ,-1 , 0
       0      .1       0  150.04     .06       0  283.65      .1       0
  310.78    .045       0   333.8      .1       0  464.76    .055       0
Bank Sta=310.78,333.8
XS Rating Curve= 0 ,0
Exp/Cntr(USF)=0,0
Exp/Cntr=0.3,0.1

Type RM Length L Ch R = 1 ,6219    ,137.4,137.2,136.9
XS GIS Cut Line= 4
2489978.93003404654775.8358757252489786.48745678654869.408872009
2489620.52780299654985.9337353062489546.37561726655049.492751651
#Sta/Elev= 30
       0 2327.74    40.2 2310.59   83.762289.182   101.2 2281.77   153.3 2257.37
  187.462244.713   226.4 2230.26   232.1 2227.17   237.8 2222.77   240.7 2221.56
   263.7  2220.1   267.4 2218.86     278 2213.15  296.122208.641  299.79 2207.33
   311.4 2205.51   318.2 2207.19   321.1 2208.31   326.1 2208.56   344.1 2207.42
   355.8  2211.9   390.6  2218.8  406.492224.538   438.6 2239.94     449 2246.15
   458.4 2253.32   467.4 2264.26   471.8 2268.57   482.3 2270.77514.4326 2279.79
#Mann= 7 ,-1 , 0
       0      .1       0   83.76      .1       0  187.46     .06       0
  296.12      .1       0  299.79    .045       0   318.2      .1       0
  406.49    .055       0
Bank Sta=299.79,318.2
XS Rating Curve= 0 ,0
Exp/Cntr(USF)=0,0
Exp/Cntr=0.3,0.1

Type RM Length L Ch R = 1 ,6082    ,109.2,109.5,109.2
XS GIS Cut Line= 4
2489825.32907788654689.3249923672489685.85234757654777.601403956
2489541.07903256654883.5330978632489449.27156451654941.795529512
#Sta/Elev= 30
       0 2292.69    26.7 2278.82    45.42271.037    69.7 2261.86    78.8 2257.36
   107.6 2245.85  139.622233.989   153.8 2227.73   165.3 2219.07   188.2 2218.46
   201.1 2212.13   213.5  2208.9     235 2206.17   243.3 2204.29   258.1 2204.63
     268 2202.79   275.6 2204.63     297 2205.62   299.9 2206.55   302.7 2208.34
   311.3 2216.42   329.8 2228.75   360.2 2243.06   367.1 2247.67  374.952251.619
   389.9 2259.82   409.4 2267.62   432.8 2275.49   446.7  2276.7453.1895 2278.92
#Mann= 6 ,-1 , 0
       0      .1       0    45.4      .1       0  139.62     .06       0
   258.1    .045       0   275.6      .1       0  374.95    .055       0
Bank Sta=258.1,275.6
XS Rating Curve= 0 ,0
Exp/Cntr(USF)=0,0
Exp/Cntr=0.3,0.1

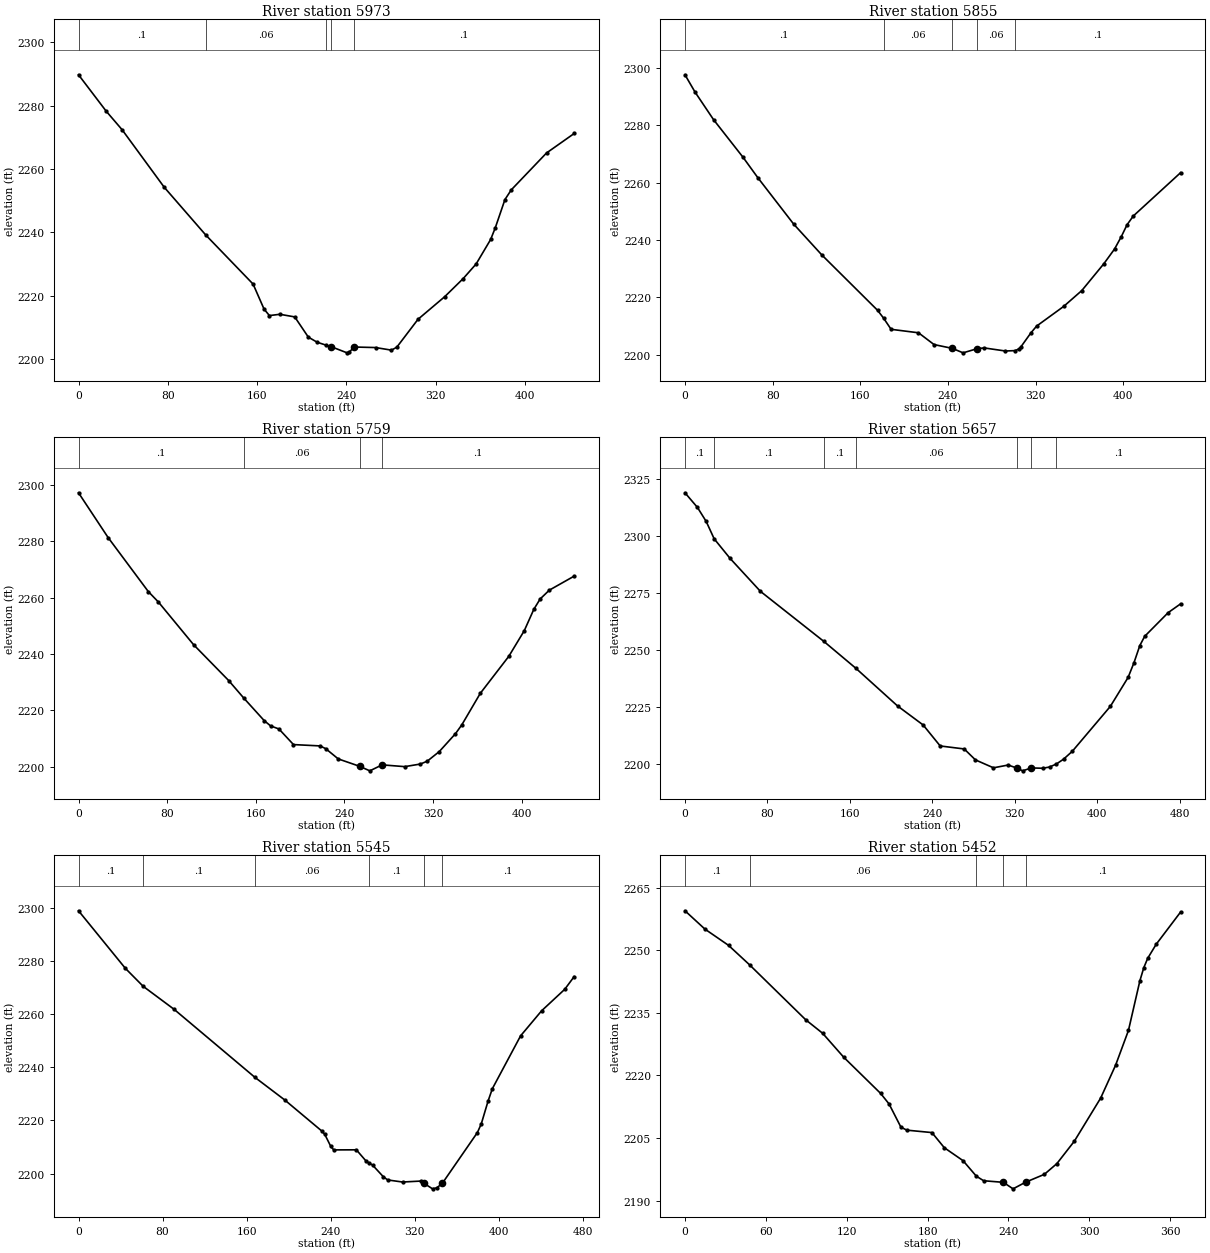
Type RM Length L Ch R = 1 ,5973    ,119.1,117.3,115.5
XS GIS Cut Line= 4
2489775.89428739654608.1106937052489625.82438769 654701.68368999
2489481.05107268654795.2566862742489403.36783048654849.988061459
#Sta/Elev= 30
       0 2289.77    24.9 2278.23    39.1  2272.4    76.8 2254.25  114.142239.117
   156.5 2223.64   166.3 2215.75   171.1  2213.7   180.5 2214.11   193.8 2213.28
     206 2206.89   213.9 2205.28  222.132204.329   226.52203.866   240.7 2201.93
   242.4 2202.09   247.2 2203.77   266.2  2203.6   280.5 2202.78   285.3 2203.72
   304.3 2212.53   328.2 2219.66   344.8 2225.39   356.4 2230.01   369.4 2237.74
   373.6 2241.47   382.2 2250.34   387.9 2253.42   419.5 2265.07444.2611 2271.22
#Mann= 5 ,-1 , 0
       0      .1       0  114.14     .06       0  222.13      .1       0
   226.5    .045       0   247.2      .1       0
Bank Sta=226.5,247.2
XS Rating Curve= 0 ,0
Exp/Cntr(USF)=0,0
Exp/Cntr=0.3,0.1

Type RM Length L Ch R = 1 ,5855    ,95.1,96.1,96.4
XS GIS Cut Line= 4
2489729.99055336654505.7100562622489564.03089958654590.455411388
2489451.03709274654689.3249923672489359.22962469654759.946121639
#Sta/Elev= 30
       0 2297.59     9.2 2291.55    26.1 2281.93      53 2268.82    66.5  2261.7
    99.3 2245.48   124.9 2234.77   175.7  2215.5  181.232212.747   188.1 2208.85
   213.1 2207.64   227.3 2203.53  243.892202.215   253.8 2200.65   266.9 2202.13
   273.1 2202.36   292.4 2201.29  301.392201.427     305 2202.06   306.6 2202.76
   315.6 2207.57   320.9 2209.98   345.6 2216.84   362.1 2222.35   382.3 2231.74
     392 2236.84   398.1  2241.1   403.4 2245.29   409.1 2248.35452.3146 2263.47
#Mann= 5 ,-1 , 0
       0      .1       0  181.23     .06       0  243.89    .045       0
   266.9     .06       0  301.39      .1       0
Bank Sta=243.89,266.9
XS Rating Curve= 0 ,0
Exp/Cntr(USF)=0,0
Exp/Cntr=0.3,0.1

Type RM Length L Ch R = 1 ,5759    ,103.4,102,100.4
XS GIS Cut Line= 4
2489682.32129111654428.0268140642489496.94082677654526.896395043
2489355.69856823654638.124673646 2489315.0914189654678.731822977
#Sta/Elev= 30
       0 2297.15    26.7 2281.28      63 2262.11    72.1 2258.41   103.8  2243.3
   135.5 2230.57  149.042224.389   167.6 2216.34   173.3 2214.49   180.9 2213.38
     194 2207.85     218 2207.38   223.1  2206.4   234.4 2202.77   253.6 2200.16
   262.9 2198.54     274 2200.66   294.4 2200.03   308.5 2200.95   314.7 2201.96
   325.6 2205.38   340.2 2211.72   345.9 2214.84   362.6 2226.03   388.3 2239.14
   402.3 2248.26   410.9 2255.82   416.6 2259.49   424.9 2262.62447.3058 2267.59
#Mann= 4 ,-1 , 0
       0      .1       0  149.04     .06       0   253.6    .045       0
     274      .1       0
Bank Sta=253.6,274
XS Rating Curve= 0 ,0
Exp/Cntr(USF)=0,0
Exp/Cntr=0.3,0.1

Type RM Length L Ch R = 1 ,5657    ,110.4,112.1,112.6
XS GIS Cut Line= 4
 2489648.7762547654316.7985354622489440.44392335654438.619983455
2489323.91906005654546.3172055932489258.59451548654593.986467851
#Sta/Elev= 30
       0 2318.94    12.1 2312.51    20.6 2306.35   28.312298.757    43.8 2290.14
    73.2 2275.71  134.762253.746   165.82241.965   206.2 2225.46   231.1 2217.09
   247.6  2207.9   270.9 2206.59   281.8 2201.79   299.3 2198.32   313.5 2199.53
     322 2198.22   327.6 2196.99     336 2198.27   347.1 2198.12   353.7 2198.67
  360.362199.994   367.3 2202.11   375.8 2205.57   412.7 2225.27   429.9 2237.95
   435.6 2244.39   441.3 2251.96     446 2255.98   468.8 2266.38480.8754 2270.24
#Mann= 7 ,-1 , 0
       0      .1       0   28.31      .1       0  134.76      .1       0
   165.8     .06       0     322    .045       0     336     .06       0
  360.36      .1       0
Bank Sta=322,336
XS Rating Curve= 0 ,0
Exp/Cntr(USF)=0,0
Exp/Cntr=0.3,0.1

Type RM Length L Ch R = 1 ,5545    ,91.6,93.1,94.4
XS GIS Cut Line= 4
2489569.32748427654253.2395191182489362.76068115654373.295438879
2489235.64264847 654473.930548092489179.14574505654516.303225653
#Sta/Elev= 30
       0 2298.78    44.6 2277.15   61.542270.401    90.9 2261.78  167.892236.196
   196.2 2227.72   231.3 2216.11   234.3 2214.82   240.1 2210.23   242.9 2208.95
   264.4 2208.98   273.7 2204.73  276.692203.951   279.8 2203.25     290 2198.89
   294.2 2197.66   308.4 2196.88   325.7 2197.24  328.852196.369   336.9 2194.32
     341 2194.71  346.182196.371   379.6 2215.48   383.3 2218.75   389.7 2227.23
   393.8 2231.93   420.7  2251.8   440.7 2261.21   462.7 2269.28471.6731 2274.06
#Mann= 6 ,-1 , 0
       0      .1       0   61.54      .1       0  167.89     .06       0
  276.69      .1       0  328.85    .045       0  346.18      .1       0
Bank Sta=328.85,346.18
XS Rating Curve= 0 ,0
Exp/Cntr(USF)=0,0
Exp/Cntr=0.3,0.1

Type RM Length L Ch R = 1 ,5452    ,103.7,103.3,102.6
XS GIS Cut Line= 4
2489451.03709274654226.7565956412489322.15353182654306.205366071
 2489198.5665556654378.5920235742489140.30412395654422.730229369
#Sta/Elev= 30
       0 2259.45    14.8 2255.06    32.3 2251.17   47.882246.513    89.6 2233.33
   102.1 2230.11   117.8 2224.35   145.1 2215.71   151.4 2213.17   160.2 2207.61
   164.6 2206.89   183.2 2206.31   192.4 2202.68   206.3 2199.58  216.212195.846
   221.6 2194.77   236.2 2194.39   243.4 2192.83   252.7 2194.42   266.6  2196.3
   275.9 2198.87   288.9 2204.26   308.4 2214.58   319.5 2222.47     329 2230.77
   337.5 2242.69   340.4 2245.82   343.3 2248.07   349.6 2251.43 367.723 2259.16
#Mann= 5 ,-1 , 0
       0      .1       0   47.88     .06       0  216.21      .1       0
   236.2    .045       0   252.7      .1       0
Bank Sta=236.2,252.7
XS Rating Curve= 0 ,0
Exp/Cntr(USF)=0,0
Exp/Cntr=0.3,0.1

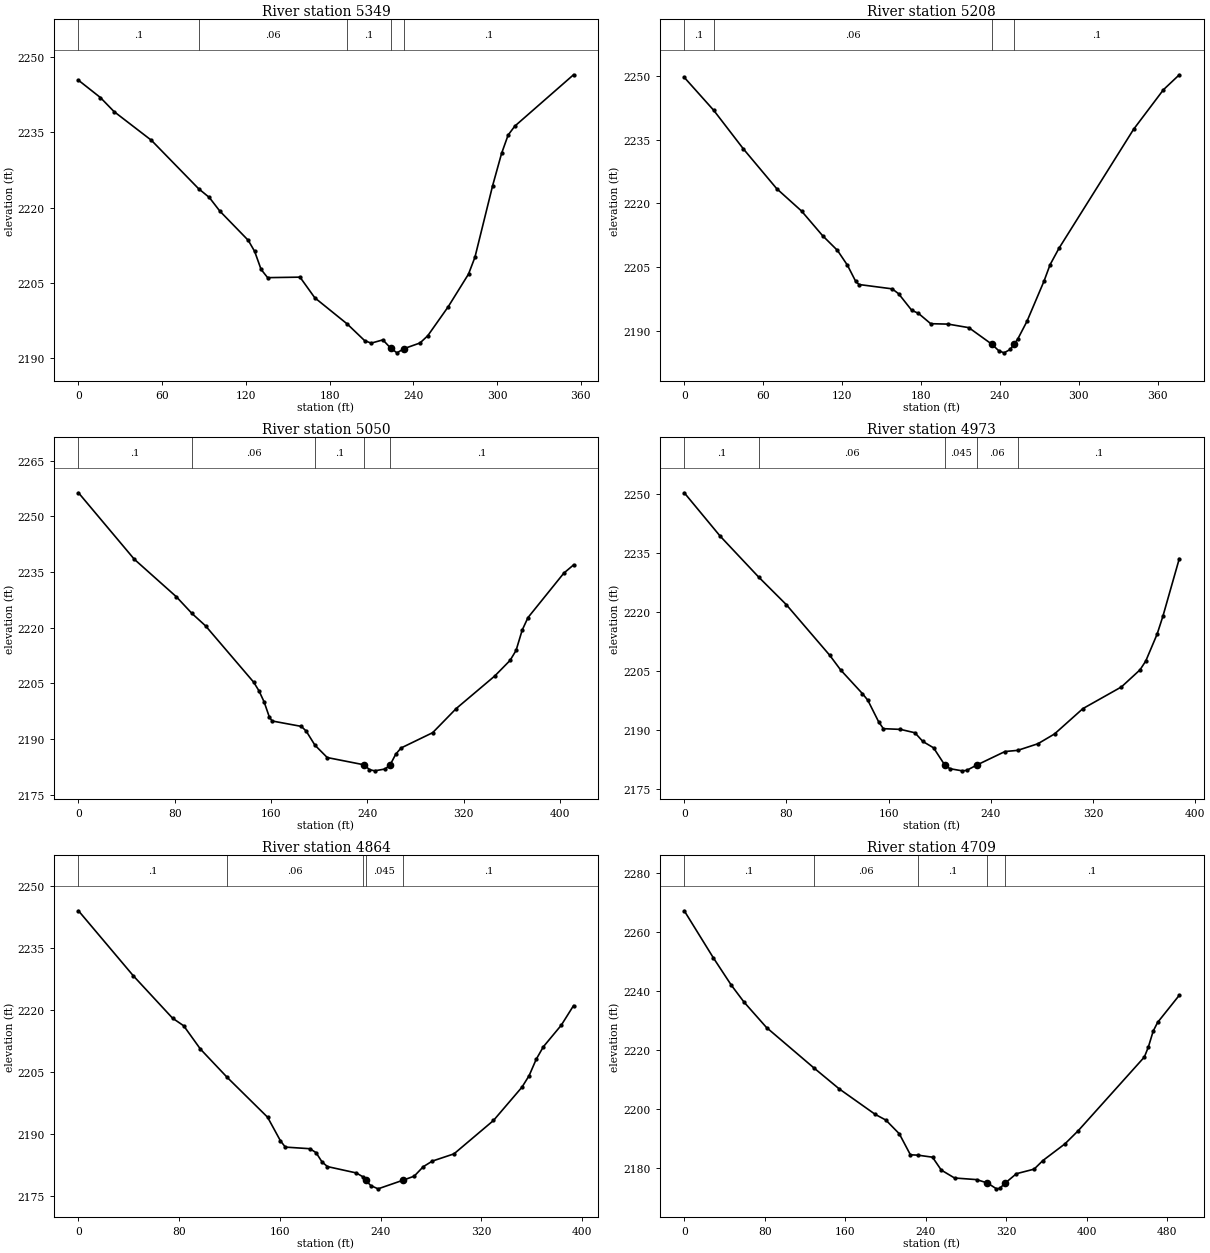
Type RM Length L Ch R = 1 ,5349    ,141.1,140.5,139.9
XS GIS Cut Line= 4
2489371.58832231654150.8388816742489299.20166481654202.039200396
2489136.77306749654297.3777249122489071.44852291654339.750402475
#Sta/Elev= 30
       0 2245.39    15.7 2241.95    25.5 2239.15    52.3 2233.43   86.042223.818
    93.8 2222.05   101.3 2219.35   121.7 2213.52   126.3 2211.31   130.9 2207.73
   135.6 2206.09   158.8 2206.19   169.4 2202.08  192.662196.864   205.1 2193.56
   209.8 2193.05   218.2  2193.7   223.7 2192.09   228.3 2191.12   233.5 2191.97
   244.8 2193.08   250.4 2194.53     265 2200.28   279.6  2206.8   284.2 2210.15
   296.9 2224.42   303.3 2230.82     308 2234.48   312.8 2236.26 354.869 2246.48
#Mann= 5 ,-1 , 0
       0      .1       0   86.04     .06       0  192.66      .1       0
   223.7    .045       0   233.5      .1       0
Bank Sta=223.7,233.5
XS Rating Curve= 0 ,0
Exp/Cntr(USF)=0,0
Exp/Cntr=0.3,0.1

Type RM Length L Ch R = 1 ,5208    ,156.2,158.6,160.7
XS GIS Cut Line= 4
2489295.67060835654034.3140183772489157.95940627654113.762788807
2489036.13795827 654205.570256862488990.23422425654251.473990886
#Sta/Elev= 30
       0 2249.64   22.462241.876      45 2232.81    70.3 2223.48    89.2 2218.22
   105.2 2212.43   116.5 2208.97   124.1 2205.48   130.4 2201.67   132.9 2200.95
   158.1 2199.93     163 2198.78     173 2194.88     178 2194.19   187.4 2191.74
   200.7 2191.64   216.4 2190.81  233.962186.902   239.2 2185.37   243.2 2184.89
   247.8 2185.68  250.762186.904   253.5 2188.07   260.6 2192.29   273.5 2201.69
   278.2 2205.62   284.9 2209.44   341.7 2237.44   364.4 2246.74376.4455 2250.25
#Mann= 4 ,-1 , 0
       0      .1       0   22.46     .06       0  233.96    .045       0
  250.76      .1       0
Bank Sta=233.96,250.76
XS Rating Curve= 0 ,0
Exp/Cntr(USF)=0,0
Exp/Cntr=0.3,0.1

Type RM Length L Ch R = 1 ,5050    ,77.2,76.7,77.4
XS GIS Cut Line= 4
2489249.76687432 653928.382324472489101.46250285653988.410284351
2488977.87552662654043.1416595362488884.30253034654111.997260575
#Sta/Elev= 30
       0 2256.37    46.4 2238.46    81.3 2228.37   94.312223.858   105.6 2220.52
   145.6 2205.34     150 2203.01   154.3    2200   158.6 2195.95   160.9  2194.9
   185.2 2193.44   189.2 2192.18  196.452188.392   206.7 2185.05  237.632183.071
   241.7  2181.8   246.1 2181.47   254.8 2181.97  258.952183.071   263.6 2185.94
     268 2187.62   294.3 2191.75   313.9 2198.26   345.9 2207.02   358.6 2211.21
   363.6  2213.9   368.7 2219.39   373.5 2222.75   403.3 2234.73411.3328 2236.93
#Mann= 5 ,-1 , 0
       0      .1       0   94.31     .06       0  196.45      .1       0
  237.63    .045       0  258.95      .1       0
Bank Sta=237.63,258.95
XS Rating Curve= 0 ,0
Exp/Cntr(USF)=0,0
Exp/Cntr=0.3,0.1

Type RM Length L Ch R = 1 ,4973    ,113.4,109.6,108.2
XS GIS Cut Line= 4
2489205.62866852653873.6509492852489052.02771236653930.147852702
 2488931.9717926 653977.817114962488847.22643747654020.189792523
#Sta/Elev= 30
       0 2250.22    28.1  2239.2   58.212228.804    79.8 2221.81   113.9  2208.9
   122.4 2205.19   139.5 2199.15   143.7 2197.48   152.2 2191.98   155.9 2190.24
   169.3 2190.06   180.6  2189.2   186.8 2186.99   195.2 2185.37  203.922181.022
   208.1 2180.06   217.6 2179.52     221 2179.62  229.232181.023   251.1 2184.43
  261.062184.726   276.9 2186.41   289.9  2188.9   312.1 2195.34   342.3 2200.86
   356.8 2205.19   361.3 2207.42   370.2 2214.26   374.7 2218.77387.5833 2233.47
#Mann= 5 ,-1 , 0
       0      .1       0   58.21     .06       0  203.92    .045       0
  229.23     .06       0  261.06      .1       0
Bank Sta=203.92,229.23
XS Rating Curve= 0 ,0
Exp/Cntr(USF)=0,0
Exp/Cntr=0.3,0.1

Type RM Length L Ch R = 1 ,4864    ,152.6,154.5,156.7
XS GIS Cut Line= 4
2489142.06965218653751.8295012922489002.59292187  653818.9195741
2488875.47488918653907.1959856892488813.68140107653963.692889106
#Sta/Elev= 30
       0    2244    43.6 2228.24    74.7    2218    83.6 2216.14    96.9 2210.49
  118.07 2203.67   150.2 2194.01   160.4 2188.31   164.3 2186.76   183.8 2186.37
   188.7 2185.43   193.5 2183.16   197.8 2182.04   220.7  2180.5  225.852179.586
  228.022178.775   232.2 2177.44     238 2176.65  258.142178.774   266.7 2179.72
   273.9 2182.01   281.1 2183.37   298.3 2185.12   329.7 2193.21   352.3 2201.27
     358 2204.07   363.6 2208.01   369.3 2211.06   383.5 2216.27393.2647 2221.02
#Mann= 5 ,-1 , 0
       0      .1       0  118.07     .06       0  225.85      .1       0
  228.02    .045       0  258.14      .1       0
Bank Sta=228.02,258.14
XS Rating Curve= 0 ,0
Exp/Cntr(USF)=0,0
Exp/Cntr=0.3,0.1

Type RM Length L Ch R = 1 ,4709    ,126.5,127.3,128
XS GIS Cut Line= 4
2489127.94542633653605.2906580542488933.73732083653702.394710802
2488746.59132826653787.1400659282488683.03231192653815.388517636
#Sta/Elev= 30
       0 2267.19    28.9 2251.28    46.8    2242    59.5 2236.25    81.8 2227.67
  128.582214.092   154.1  2206.9   189.9 2198.27   200.4 2196.36   213.8  2191.7
   224.8 2184.61  232.46 2184.47   246.8 2183.79   255.5 2179.43   268.7 2176.75
   290.7  2176.2  301.422175.056   310.4 2173.08   313.5 2173.21  319.122175.054
   330.2  2178.2   347.8 2179.75   356.5 2182.65   378.5 2188.32   391.7 2192.77
   457.4 2217.69   461.4 2221.11   466.2 2226.48   470.6 2229.42492.1245  2238.6
#Mann= 5 ,-1 , 0
       0      .1       0  128.58     .06       0  232.46      .1       0
  301.42    .045       0  319.12      .1       0
Bank Sta=301.42,319.12
XS Rating Curve= 0 ,0
Exp/Cntr(USF)=0,0
Exp/Cntr=0.5,0.3

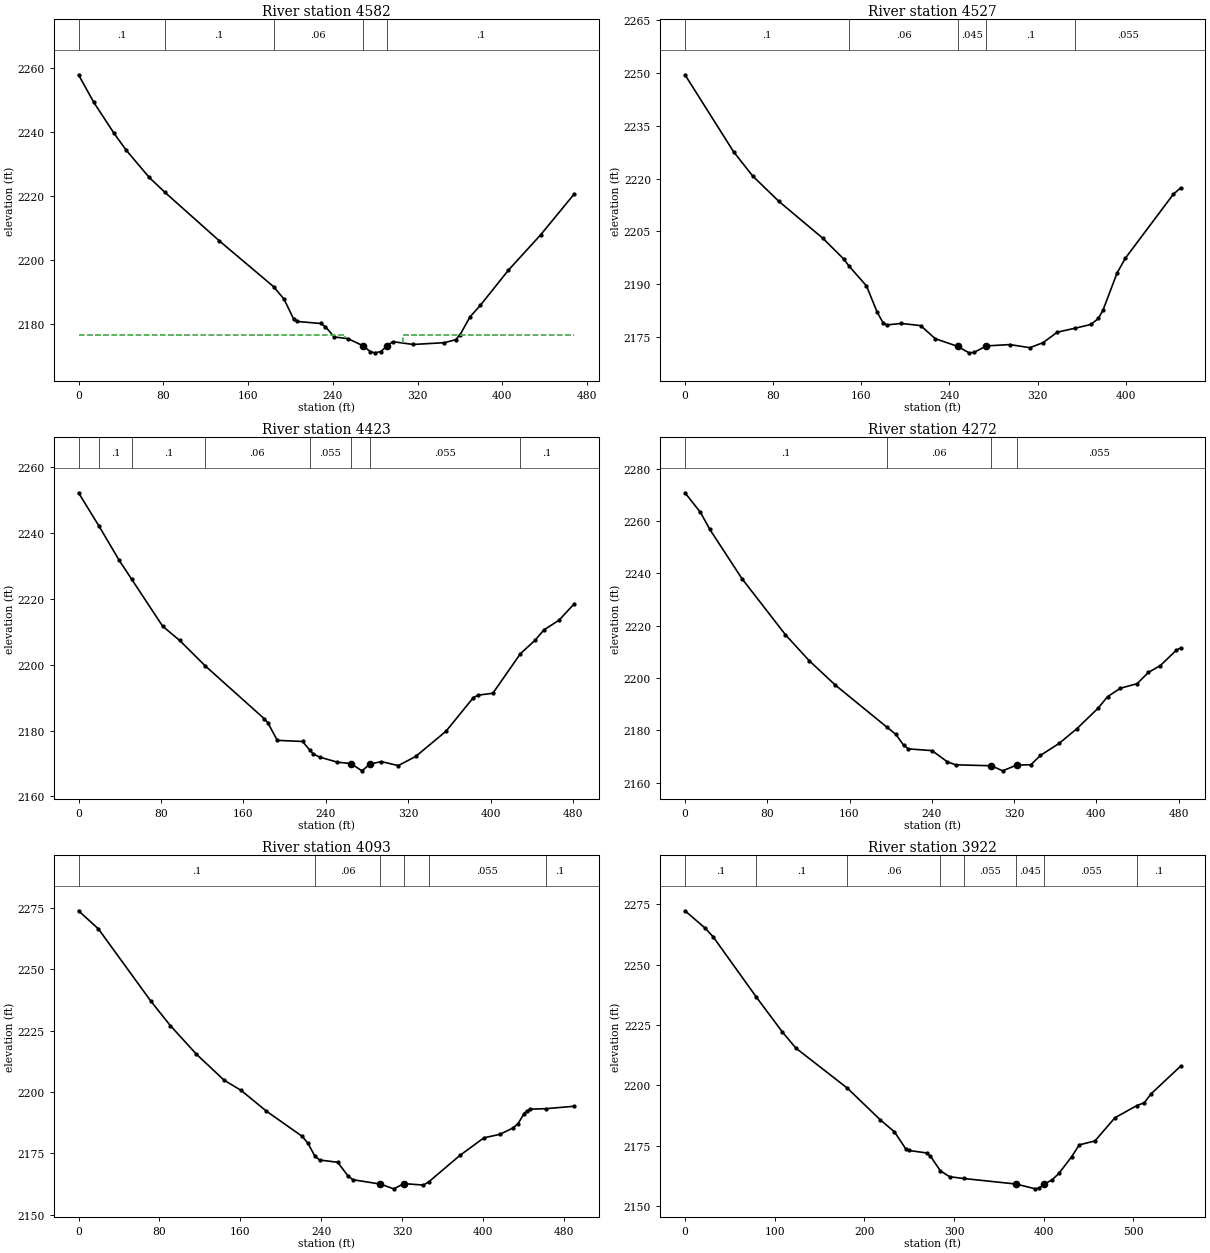
Type RM Length L Ch R = 1 ,4582    ,55.9,54.9,53.8
XS GIS Cut Line= 4
2489067.91746645 653511.717661772488875.47488918653598.228545127
2488720.10840478653652.9599203122488642.42516259653702.394710802
#Sta/Elev= 30
       0 2257.83    14.4 2249.22    33.5 2239.53    45.1 2234.21    66.8  2225.7
   81.212221.161   132.9 2205.88  184.032191.573   193.9 2187.69     203 2181.46
     206 2180.68   228.7 2180.03     233 2179.02   241.5  2175.8   254.2 2175.31
  268.372173.081   275.4 2171.23   279.6 2170.85   285.2 2171.22   291.52173.083
   296.6 2174.34   315.9 2173.47   345.4 2174.03     356 2174.96   360.2 2176.57
   369.5 2182.11   379.3 2185.73   405.8 2196.74   436.1 2207.74467.7971 2220.52
#Mann= 5 ,-1 , 0
       0      .1       0   81.21      .1       0  184.03     .06       0
  268.37    .045       0   291.5      .1       0
#XS Ineff= 2 , 0
          251.59 2176.58  305.92         2176.55
Permanent Ineff=
       F       F
Bank Sta=268.37,291.5
XS Rating Curve= 0 ,0
Exp/Cntr(USF)=0,0
Exp/Cntr=0.5,0.3

Type RM Length L Ch R = 1 ,4527    ,103.2,104.2,103.9
XS GIS Cut Line= 4
2489027.31031711653467.5794559752488864.88171979653536.435057015
2488716.57734832653603.5251298232488612.41118265 653640.60122269
#Sta/Elev= 30
       0 2249.54    44.1 2227.66    61.4 2220.77    85.3 2213.52     125 2203.08
     144 2197.17  149.022195.083   164.7 2189.51   174.4 2182.03   179.9 2178.93
   183.2 2178.41   196.3 2178.83   213.9 2178.21   227.1 2174.49  247.362172.318
   257.8 2170.47   262.2 2170.58   273.6 2172.44   294.8 2172.82   312.9 2171.93
     325 2173.37   337.7 2176.33  354.332177.502   368.3 2178.53   375.1 2180.24
   379.4 2182.66   392.1 2193.19   399.6 2197.38     443 2215.51449.7618  2217.4
#Mann= 5 ,-1 , 0
       0      .1       0  149.02     .06       0  247.36    .045       0
   273.6      .1       0  354.33    .055       0
#XS Ineff= 2 , 0
             217 2171.55     303         2171.55
Permanent Ineff=
       F       F
Bank Sta=247.36,273.6
XS Rating Curve= 0 ,0
Exp/Cntr(USF)=0,0
Exp/Cntr=0.5,0.3

Type RM Length L Ch R = 1 ,4423    ,152.4,150.5,149
XS GIS Cut Line= 4
2488986.78793251653381.3180231092488836.63326808653449.129807046
2488642.88531398653514.5197415562488546.01133693653570.222278361
#Sta/Elev= 30
       0  2252.2   19.922242.062    39.5 2231.68   51.742225.878    81.6  2211.7
      98  2207.4  122.78 2199.69   180.3 2183.57   183.6 2182.42   192.9 2177.02
   217.4 2176.68  224.352174.086   227.6 2172.91   233.9 2171.95   251.2 2170.39
  264.272169.976     275 2167.76   282.8  2169.8   293.9 2170.57   310.3 2169.35
   327.2 2172.13   356.7 2179.81   383.2 2190.01   387.9 2190.74   402.1 2191.33
  428.782203.318   443.2 2207.47   451.6 2210.55   466.3  2213.5480.9887 2218.46
#Mann= 8 ,-1 , 0
       0      .1       0   19.92      .1       0   51.74      .1       0
  122.78     .06       0  224.35    .055       0  264.27    .045       0
   282.8    .055       0  428.78      .1       0
Bank Sta=264.27,282.8
XS Rating Curve= 0 ,0
Exp/Cntr(USF)=0,0
Exp/Cntr=0.5,0.3

Type RM Length L Ch R = 1 ,4272    ,180.9,179,174.5
XS GIS Cut Line= 4
2488923.81984743653204.5230149892488739.75929103 653308.66254032
2488596.87017488653388.583571388 2488507.2617461 653446.70795762
#Sta/Elev= 30
       0 2270.79      15 2263.33    24.2 2256.78    55.4    2238    97.7 2216.57
   120.7  2206.7   146.3  2197.3  196.172181.329   205.1 2178.51   212.6 2174.39
   217.2 2172.97   240.3  2172.3     255 2168.06   263.1 2166.88     298 2166.52
   308.9 2164.58   322.6  2166.8   322.6 2166.81   336.4 2166.89   345.6 2170.45
   363.8 2175.05   381.3 2180.74   401.5 2188.42   411.1 2192.96   423.5 2196.14
   439.7 2197.88   450.7 2202.19   462.3  2204.8   477.9 2210.69 482.009 2211.51
#Mann= 4 ,-1 , 0
       0      .1       0  196.17     .06       0     298    .045       0
   322.6    .055       0
Bank Sta=298,322.6
XS Rating Curve= 0 ,0
Exp/Cntr(USF)=0,0
Exp/Cntr=0.3,0.1

Type RM Length L Ch R = 1 ,4093    ,165.9,171.6,160.8
XS GIS Cut Line= 4
2488822.10217152653022.884308015 2488635.6197657653148.820478183
2488499.99619783653252.9600035152488429.76256446653315.928088599
#Sta/Elev= 30
       0 2273.87    19.7 2266.48    71.6 2237.04    90.9 2227.07   116.5  2215.5
     144 2204.87   160.9 2200.68   185.8 2192.27   221.3 2181.97   227.1 2179.08
  233.812173.923   238.5 2172.35   256.4  2171.4   266.5 2165.91   271.5  2164.3
  298.492162.543   311.9 2160.59   321.9 2162.72   341.2 2162.12  346.622163.477
   377.4 2174.24   401.1 2181.38   416.9  2182.8   429.9  2185.4   434.9 2187.18
   440.8 2191.27   443.6 2192.33   446.8 2193.04  462.332193.249 490.345 2194.23
#Mann= 6 ,-1 , 0
       0      .1       0  233.81     .06       0  298.49    .045       0
   321.9     .06       0  346.62    .055       0  462.33      .1       0
Bank Sta=298.49,321.9
XS Rating Curve= 0 ,0
Exp/Cntr(USF)=0,0
Exp/Cntr=0.3,0.1

Type RM Length L Ch R = 1 ,3922    ,131.1,135.1,136.3
XS GIS Cut Line= 4
2488776.08703242652955.0725240792488546.01133693653042.259103426
2488361.95078053653160.9297253152488294.13899659 653216.63226212
#Sta/Elev= 30
       0 2272.24    22.1  2265.2    31.4 2261.48    79.72236.469   108.4 2222.19
   123.7 2215.41  181.062198.854     218 2185.66   233.6 2180.76     246 2173.85
   249.9 2173.04   269.4 2172.03   273.7 2170.71  284.952164.592   295.2 2162.18
  310.822161.449   369.32159.159   390.7 2157.17   394.8 2157.44  400.772159.161
   409.6 2160.92     417 2163.56   431.2 2170.42   439.8 2175.38   457.2 2176.98
   479.5 2186.58  503.92 2191.61   512.2 2192.79   519.9 2196.51552.7979 2207.95
#Mann= 8 ,-1 , 0
       0      .1       0    79.7      .1       0  181.06     .06       0
  284.95      .1       0  310.82    .055       0   369.3    .045       0
  400.77    .055       0  503.92      .1       0
Bank Sta=369.3,400.77
XS Rating Curve= 0 ,0
Exp/Cntr(USF)=0,0
Exp/Cntr=0.3,0.1

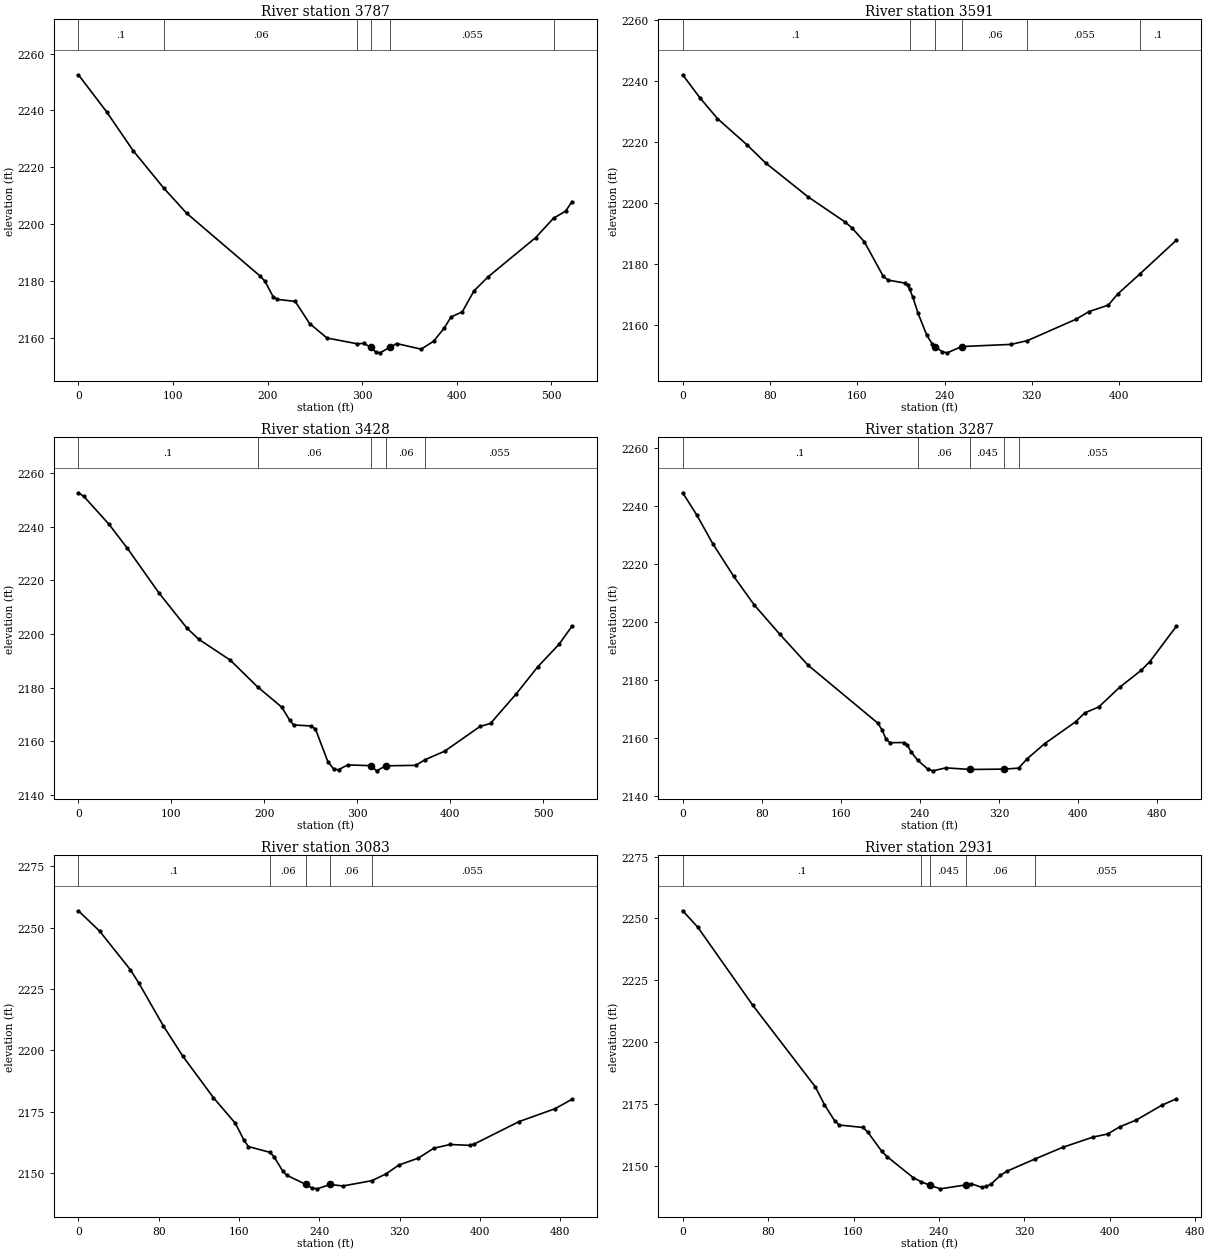
Type RM Length L Ch R = 1 ,3787    ,196.2,195.9,181.3
XS GIS Cut Line= 4
2488671.94750709 652875.151493012488514.52729438652942.963276947
2488291.71714716653037.4154045732488197.26501954653090.696091952
#Sta/Elev= 30
       0 2252.53    29.7 2239.54    57.9  2225.8   90.11 2212.66   114.5 2203.74
   191.7 2181.76   197.2 2179.85   205.9 2174.34   210.3 2173.44   229.2 2172.72
   244.4 2164.93   262.7 2159.84  294.722157.795   301.5 2157.93  309.092156.595
   314.5 2154.85   318.9 2154.61   329.5 2156.62   336.3 2157.88   362.3 2155.91
   375.4 2158.68   386.4 2163.19   393.9 2167.23   405.8 2169.05   418.1  2176.4
   432.9 2181.32   483.4  2195.2  502.242202.012     515 2204.51521.8516 2207.89
#Mann= 6 ,-1 , 0
       0      .1       0   90.11     .06       0  294.72    .055       0
  309.09    .045       0   329.5    .055       0  502.24      .1       0
Bank Sta=309.09,329.5
XS Rating Curve= 0 ,0
Exp/Cntr(USF)=0,0
Exp/Cntr=0.3,0.1

Type RM Length L Ch R = 1 ,3591    ,165.2,163.1,151.2
XS GIS Cut Line= 4
2488565.38613234652720.1531297272488400.70037135652785.543064237
2488240.85830921652867.8859447312488153.67172986652906.635535552
#Sta/Elev= 30
       0 2241.97    15.8 2234.42    31.9  2227.6    58.8 2219.06      76 2213.07
   114.7 2202.02   148.9  2193.7   155.1  2191.8   166.4 2187.28   183.9 2175.86
   188.6 2174.65   203.4 2173.73   206.4 2172.97  207.862171.762   210.9 2169.15
   215.7  2163.8   223.8 2156.53   228.9 2153.66  231.152152.903   237.9 2151.18
   242.4 2150.84  255.652152.904   300.9 2153.61  315.942154.843   360.9 2161.93
   372.4 2164.37     390 2166.47   398.7 2170.13  419.332176.809452.4075 2187.74
#Mann= 6 ,-1 , 0
       0      .1       0  207.86     .06       0  231.15    .045       0
  255.65     .06       0  315.94    .055       0  419.33      .1       0
Bank Sta=231.15,255.65
XS Rating Curve= 0 ,0
Exp/Cntr(USF)=0,0
Exp/Cntr=0.3,0.1

Type RM Length L Ch R = 1 ,3428    ,138,140.7,143.8
XS GIS Cut Line= 4
2488524.21469209652567.5766158692488298.98269544652649.919496363
2488160.93727814652751.6371722692488076.17254822652836.401902189
#Sta/Elev= 30
       0 2252.59     5.8 2251.25      33 2240.82    52.7 2231.89    86.7 2215.26
   116.6 2202.24   129.3 2198.07   163.4 2190.24  192.882180.242   218.8 2172.74
   227.3 2167.87   231.5 2166.12     250 2165.72     255 2164.62   268.4 2152.41
     275 2149.56   279.9 2149.44   289.8 2151.22   314.6 2150.94   320.8 2149.01
   330.8 2150.89   362.8 2151.05  373.352153.219   394.1 2156.33   432.1 2165.54
   443.4 2166.67     471 2177.65   494.3 2187.79     517  2196.1531.1605 2202.93
#Mann= 5 ,-1 , 0
       0      .1       0  192.88     .06       0   314.6    .045       0
   330.8     .06       0  373.35    .055       0
Bank Sta=314.6,330.8
XS Rating Curve= 0 ,0
Exp/Cntr(USF)=0,0
Exp/Cntr=0.3,0.1

Type RM Length L Ch R = 1 ,3287    ,199.6,204.1,193.1
XS GIS Cut Line= 4
2488456.40290815652482.8118859482488248.12385749652543.358121606
 2488093.1254942652608.7480561162487996.25151715652669.294291774
#Sta/Elev= 30
       0 2244.62    14.2 2236.99    30.4 2227.07    51.7 2215.74    72.5 2205.88
    98.2 2195.82   126.7 2185.17   197.5  2165.1   201.7 2162.76   205.8 2159.51
     210 2158.39   223.7 2158.45   227.1 2157.57   231.4 2155.06  237.562152.396
   248.1 2149.23   253.1 2148.68   266.2 2149.71   290.9 2149.15   325.5 2149.28
  339.772149.617   348.6 2152.89     366 2158.01   397.4 2165.59   406.8 2168.68
     421 2170.75     442 2177.51   463.9 2183.39   472.6 2186.39499.3664 2198.55
#Mann= 5 ,-1 , 0
       0      .1       0  237.56     .06       0   290.9    .045       0
   325.5     .06       0  339.77    .055       0
Bank Sta=290.9,325.5
XS Rating Curve= 0 ,0
Exp/Cntr(USF)=0,0
Exp/Cntr=0.3,0.1

Type RM Length L Ch R = 1 ,3083    ,154.9,152.2,143.6
XS GIS Cut Line= 4
2488374.06002766652289.0639318432488223.90536323652354.453866354
2488059.21960224652417.4219514382487923.59603436652485.233735374
#Sta/Elev= 30
       0 2256.83    21.1 2248.56    51.6  2232.9    60.3 2227.31    84.7 2209.89
     104 2197.63   134.5 2180.73   156.3  2170.3     165 2163.36   169.3 2160.81
  190.732158.487     195 2156.61   203.6 2150.78   207.8 2149.08  226.422145.444
   232.2 2144.04   237.8 2143.61   250.7 2145.38   263.5 2144.78  292.162146.923
   306.3 2149.65   319.2 2153.31   338.4 2156.08     354 2160.15   370.2 2161.67
   389.8 2161.31   394.3 2161.86     439 2171.01   474.8 2176.24491.7201 2180.09
#Mann= 5 ,-1 , 0
       0      .1       0  190.73     .06       0  226.42    .045       0
   250.7     .06       0  292.16    .055       0
Bank Sta=226.42,250.7
XS Rating Curve= 0 ,0
Exp/Cntr(USF)=0,0
Exp/Cntr=0.3,0.1

Type RM Length L Ch R = 1 ,2931    ,184.6,185.2,184.8
XS GIS Cut Line= 4
 2488277.1860506652146.1748156912488102.81289191652235.783244464
2487972.03302289652313.2824261062487880.00274469652381.094210043
#Sta/Elev= 30
       0 2253.07    14.2  2246.4    65.7 2214.83   124.2  2181.9   132.8 2174.64
   142.2 2168.25   146.7 2166.43   169.1 2165.44   173.6 2163.44   186.5 2155.77
   191.6  2153.6   215.9 2145.18  223.092143.546  231.452142.081   241.4 2140.63
   264.9  2142.2   270.5 2142.64   280.1 2141.26   284.5  2141.6   288.9 2142.59
   297.6 2146.04   303.5 2147.73  329.792152.666   355.9 2157.41   384.4 2161.56
     398  2162.8   409.3  2165.7     425 2168.48     449 2174.49462.3836 2177.02
#Mann= 5 ,-1 , 0
       0      .1       0  223.09     .06       0  231.45    .045       0
   264.9     .06       0  329.79    .055       0
Bank Sta=231.45,264.9
XS Rating Curve= 0 ,0
Exp/Cntr(USF)=0,0
Exp/Cntr=0.3,0.1