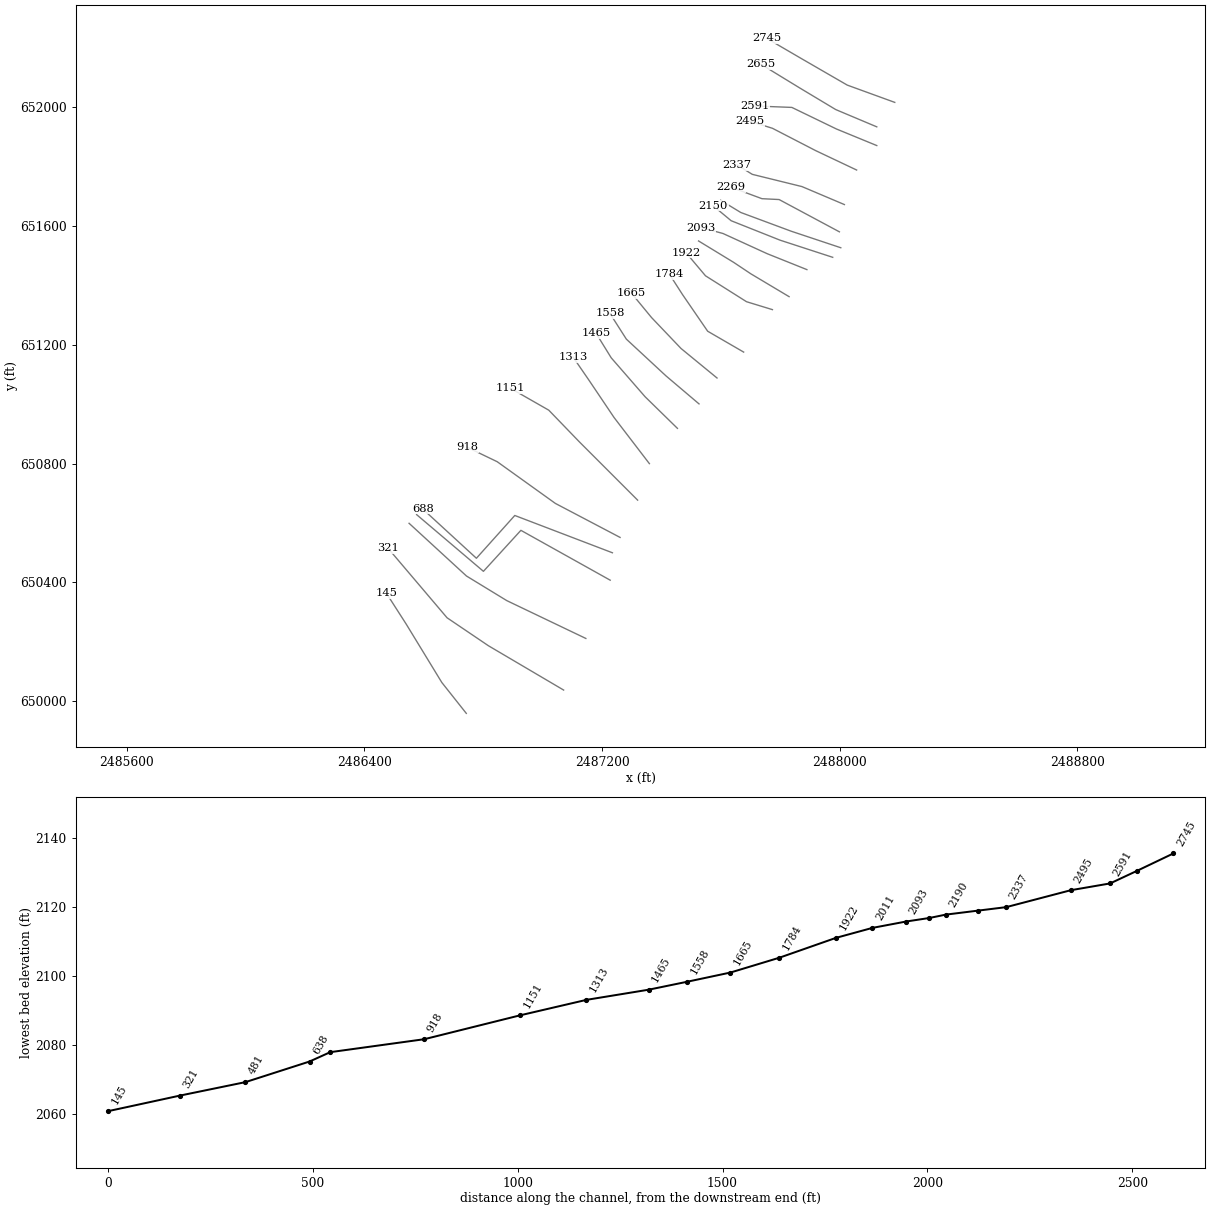
HEC-RAS study SHAVERN.prj: SHAVERN

--- SHAVERN.g01 (geometry) --- (continued)

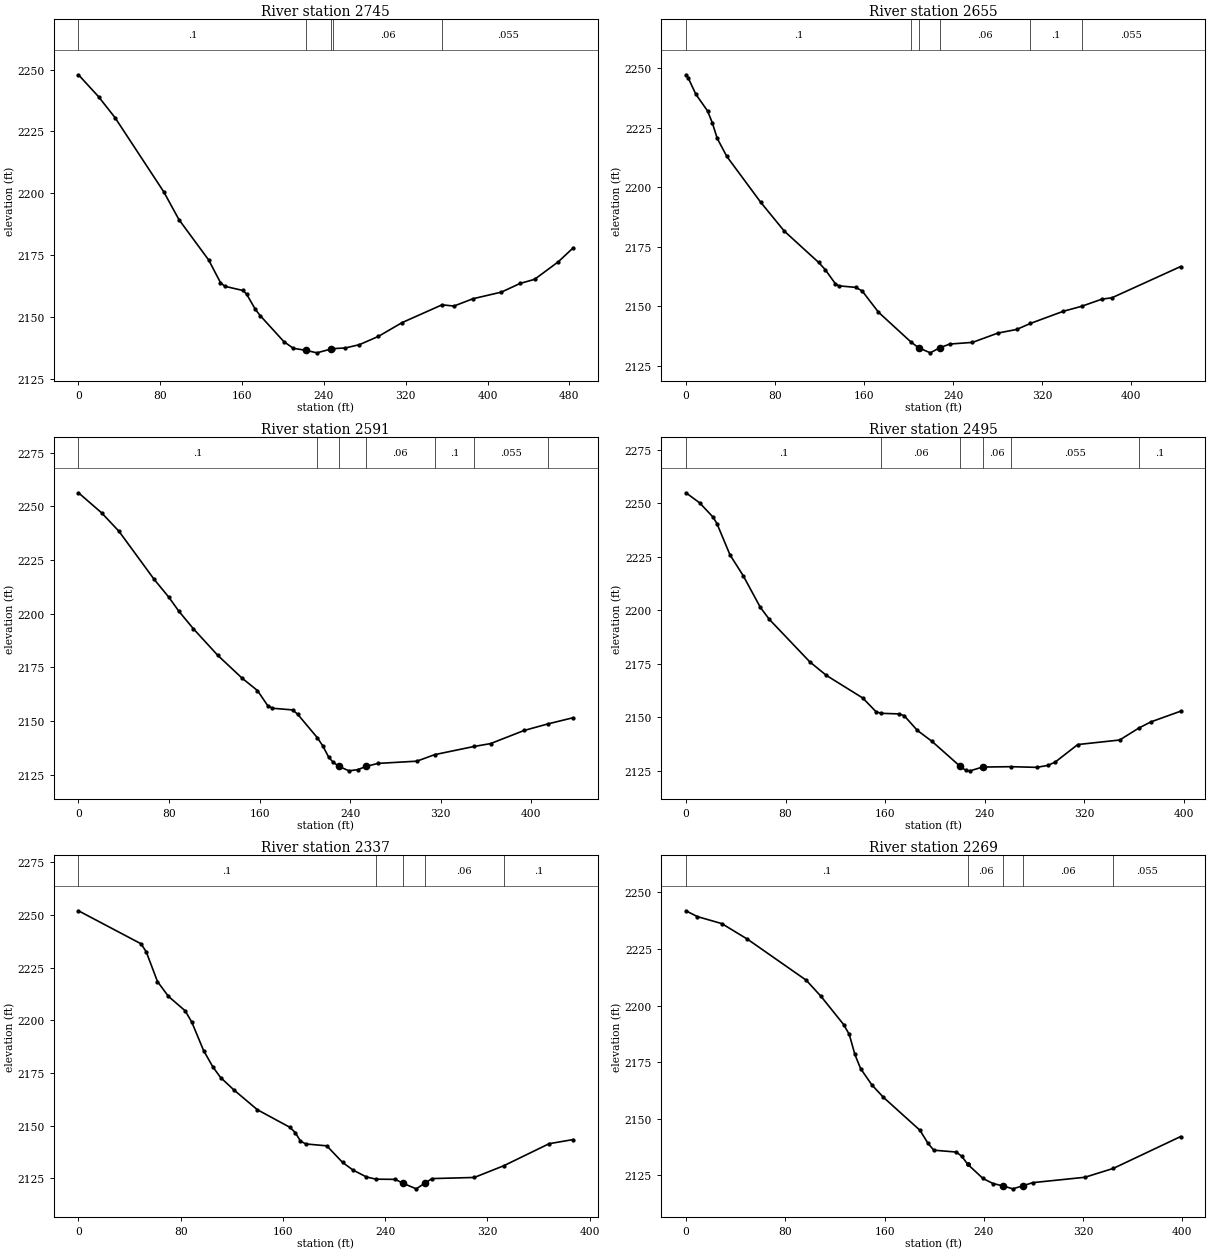
Type RM Length L Ch R = 1 ,2745    ,90.2,90.1,90.1
XS GIS Cut Line= 4
 2488185.1557724 652015.394946672488025.31371027652073.519332902
2487870.31534698652163.1277616752487754.06657452652230.939545612
#Sta/Elev= 30
       0  2247.9    19.6 2239.06    35.8 2230.54    83.4 2200.57    98.2 2189.38
   127.3 2173.03   138.8 2163.93     143 2162.41   160.7 2160.71   164.3 2159.28
     173 2153.04   177.7 2150.53   200.8 2140.05     210 2137.34   222.7 2136.49
   233.1  2135.5  247.072137.055   249.22137.204     261 2137.48   274.7 2138.81
   293.2 2142.14   316.4 2147.72  355.472154.909   367.1 2154.41   385.7 2157.37
   413.5 2160.05     432 2163.59   445.9  2165.2     469 2172.26483.7005 2177.95
#Mann= 5 ,-1 , 0
       0      .1       0   222.7    .045       0  247.07      .1       0
   249.2     .06       0  355.47    .055       0
Bank Sta=222.7,247.07
XS Rating Curve= 0 ,0
Exp/Cntr(USF)=0,0
Exp/Cntr=0.3,0.1

Type RM Length L Ch R = 1 ,2655    ,63.5,64.4,64.9
XS GIS Cut Line= 4
2488124.60953675651933.0520661762487986.56411945651991.176452407
2487865.47164813652063.8319351962487734.69177911652143.752966265
#Sta/Elev= 30
       0 2247.19       2 2245.91     8.9 2239.01    19.4 2232.01    23.7    2227
    28.1 2220.46    36.7  2212.9    67.1 2193.66    88.3 2181.53   119.2 2168.35
     125 2165.39   134.2 2159.41   137.2 2158.54   152.4 2157.89   158.2 2156.42
   172.9 2147.46  202.412134.793  209.122132.488   219.4 2130.39  227.822132.489
   236.9 2134.08   257.3 2134.78   280.2  2138.7   296.9  2140.2   309.42142.754
   338.9 2147.85  355.232149.932   373.6 2152.95   382.5 2153.51444.2669 2166.65
#Mann= 6 ,-1 , 0
       0      .1       0  202.41     .06       0  209.12    .045       0
  227.82     .06       0   309.4      .1       0  355.23    .055       0
Bank Sta=209.12,227.82
XS Rating Curve= 0 ,0
Exp/Cntr(USF)=0,0
Exp/Cntr=0.3,0.1

Type RM Length L Ch R = 1 ,2591    ,96.4,95.8,95.2
XS GIS Cut Line= 4
2488124.60953675651870.0839810922487988.98596887651925.786517897
2487838.83130444651998.442000686 2487715.3169837652003.285699539
#Sta/Elev= 30
       0 2256.32    20.4    2247    35.8 2238.37    66.9 2215.96    79.9 2207.63
    88.5 2201.28   101.5 2192.99   123.1 2180.58   144.7  2169.9   158.1 2164.22
   167.1 2157.23   171.3 2155.97   189.1 2155.19   193.5 2153.25  211.042142.216
   215.8 2138.44     221 2133.23   224.6    2131  230.052128.875     239 2126.81
   246.9 2127.38  254.042128.875   264.6 2130.27   298.9 2131.31  314.642134.351
   349.62138.179     364 2139.49   393.6  2145.6  414.692148.667437.0352 2151.56
#Mann= 7 ,-1 , 0
       0      .1       0  211.04     .06       0  230.05    .045       0
  254.04     .06       0  314.64      .1       0   349.6    .055       0
  414.69      .1       0
Bank Sta=230.05,254.04
XS Rating Curve= 0 ,0
Exp/Cntr(USF)=0,0
Exp/Cntr=0.3,0.1

Type RM Length L Ch R = 1 ,2495    ,154.9,157.6,159.2
XS GIS Cut Line= 4
2488056.79775281651787.7411005972487918.75233551651853.131035107
2487773.44136993651928.2083673232487695.94218829651952.426861586
#Sta/Elev= 30
       0 2254.84    11.1  2250.1    21.9 2243.38    24.9 2240.45    35.4 2225.81
      46  2216.1    59.8 2201.25      67 2195.67    99.6 2175.75   112.9 2169.44
   142.1 2158.89   152.8 2152.45  156.992151.741   170.8 2151.47   175.3 2150.67
   185.9 2143.77   197.8 2138.58  220.432126.889   224.8  2125.1   228.3 2124.85
   238.3 2126.62  261.492126.789   281.7 2126.48   290.6 2127.36   296.6  2128.9
   314.8 2137.14   348.5 2139.26     3642144.887   373.6 2147.74397.5046 2152.74
#Mann= 6 ,-1 , 0
       0      .1       0  156.99     .06       0  220.43    .045       0
   238.3     .06       0  261.49    .055       0     364      .1       0
Bank Sta=220.43,238.3
XS Rating Curve= 0 ,0
Exp/Cntr(USF)=0,0
Exp/Cntr=0.3,0.1

Type RM Length L Ch R = 1 ,2337    ,66.1,68.1,69.8
XS GIS Cut Line= 4
2488015.62631256651671.4923281342487872.73719641651732.038563792
2487705.62958599651773.2100040392487654.77074804651804.694046581
#Sta/Elev= 30
       0 2251.99      49  2236.3    53.1  2232.4    61.8  2218.4    70.4 2211.35
    83.5 2204.49    88.7 2199.06    97.9 2185.63   105.2 2177.81   111.2 2172.82
   121.5 2166.98     140 2157.51   165.5 2149.14   169.6 2146.67   173.7 2142.67
   177.8 2141.27   194.3 2140.37   206.7 2132.46   214.9 2128.84   225.3  2125.6
  232.752124.544   247.9 2124.45  253.952122.581   264.3 2119.95  270.832122.579
   276.7 2124.82   309.7 2125.35  332.792130.921   368.3 2141.39387.1075 2143.35
#Mann= 5 ,-1 , 0
       0      .1       0  232.75     .06       0  253.95    .045       0
  270.83     .06       0  332.79      .1       0
Bank Sta=253.95,270.83
XS Rating Curve= 0 ,0
Exp/Cntr(USF)=0,0
Exp/Cntr=0.3,0.1

Type RM Length L Ch R = 1 ,2269    ,82,79.5,75.7
XS GIS Cut Line= 4
 2487998.7536104651579.7659850142487795.91796899651688.393603401
2487738.23958754651691.2775224732487634.41850094 651729.72977677
#Sta/Elev= 30
       0 2241.91     9.1 2239.36    28.9 2236.24    49.6 2229.34    96.9 2211.21
   108.9 2204.02   127.1 2191.57   131.6 2187.22   136.1  2178.4   140.7 2172.15
   149.7 2164.99   158.9 2159.53   188.5 2144.87   195.1 2139.02   199.7 2136.04
   217.8 2135.22   222.3  2133.3   226.9  2129.9   226.9 2129.88   226.9 2129.87
   226.9 2129.86   239.3 2123.55   247.3 2121.31   255.7 2120.22   263.3 2118.95
   271.3 2120.26   279.4 2121.69   321.4 2124.06   344.3 2127.98   398.6 2142.08
#Mann= 5 ,-1 , 0
       0      .1       0   226.9     .06       0   255.7    .045       0
   271.3     .06       0   344.3    .055       0
Bank Sta=255.7,271.3
XS Rating Curve= 0 ,0
Exp/Cntr(USF)=0,0
Exp/Cntr=0.3,0.1

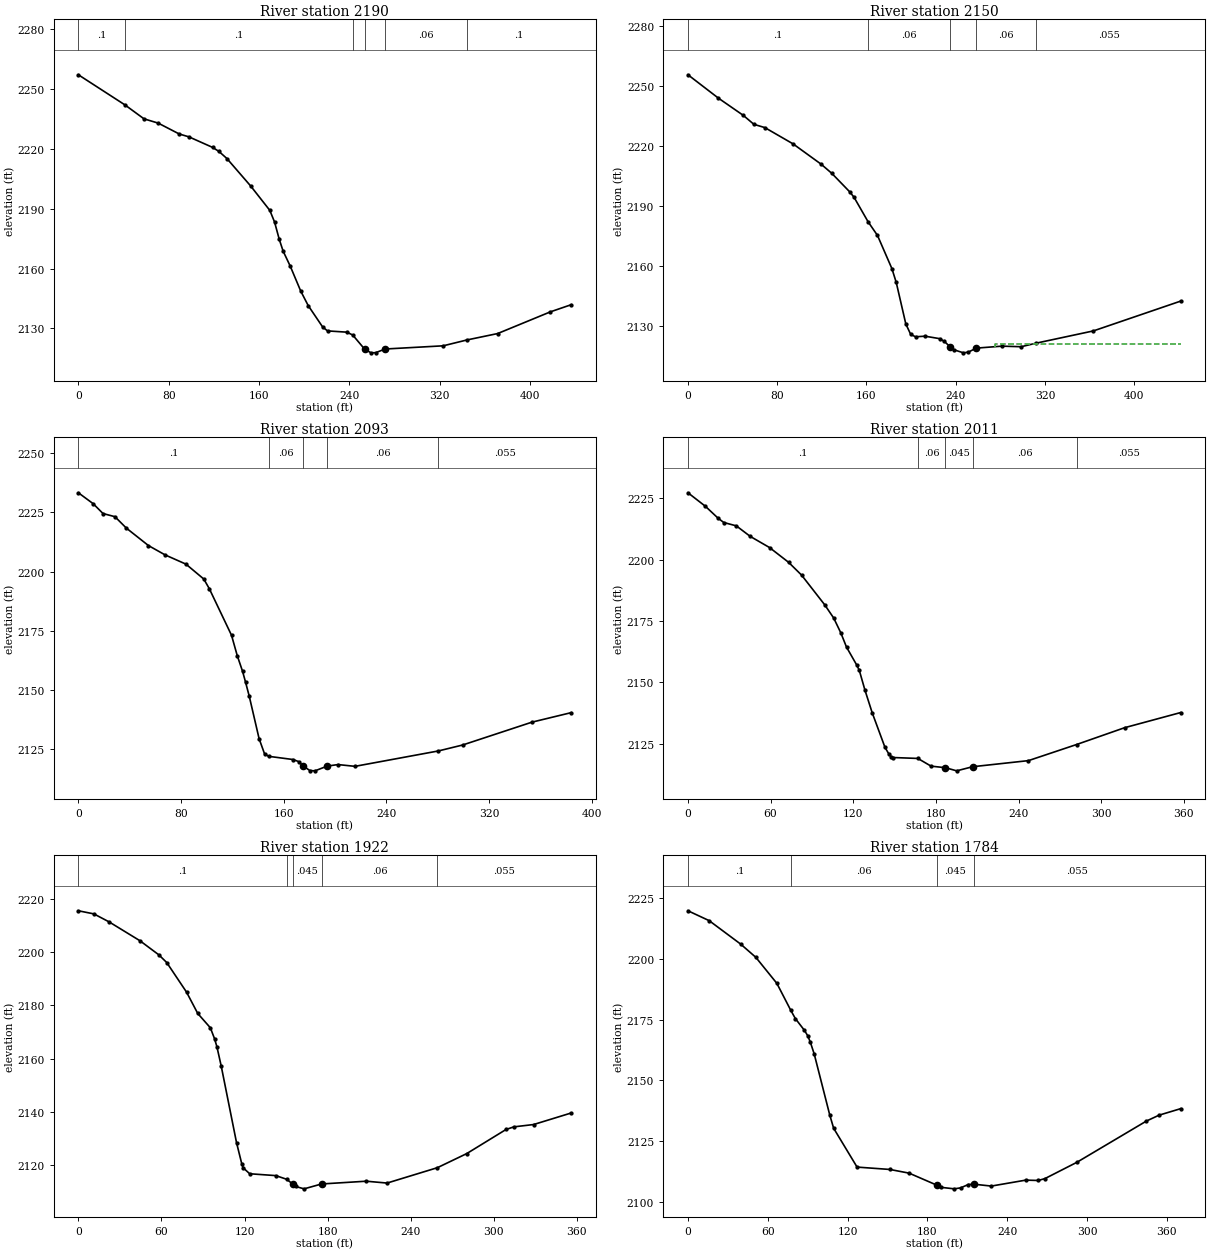
Type RM Length L Ch R = 1 ,2190    ,40.1,40,39.7
XS GIS Cut Line= 4
2488003.51706543651526.1813625552487836.40945502651581.883899361
2487666.87999517651644.8519844452487599.06821124651686.023424692
#Sta/Elev= 30
       0 2257.14   41.25 2242.04    58.1 2235.06    70.7 2232.91    89.4 2227.44
    97.8 2226.05   118.9 2220.73   124.5 2218.71   131.5 2215.17   152.6 2201.37
   169.5 2189.19   173.7 2183.36   177.9 2174.59   181.3 2168.75   187.6 2161.22
   196.9 2148.71   203.5 2141.46   216.3 2130.73   220.6 2128.78   237.7 2128.14
  242.892126.723  253.342119.698   259.1 2117.78   263.3 2117.87  271.582119.697
     323  2121.3  344.122124.247   371.2 2127.44     418 2138.34436.3245  2141.9
#Mann= 6 ,-1 , 0
       0      .1       0   41.25      .1       0  242.89     .06       0
  253.34    .045       0  271.58     .06       0  344.12      .1       0
#XS Ineff= 2 , 0
             203 2121.18     321         2121.18
Permanent Ineff=
       F       F
Bank Sta=253.34,271.58
XS Rating Curve= 0 ,0
Exp/Cntr(USF)=0,0
Exp/Cntr=0.5,0.3

Type RM Length L Ch R = 1 ,2150    ,56.9,56.5,55.9
XS GIS Cut Line= 4
2487976.29897622651493.973726185 2487799.0244449651551.702896328
2487634.52185387651617.0952306492487574.23829567651667.161236614
#Sta/Elev= 30
       0  2255.7    27.3 2244.02    49.6 2235.42    59.1 2230.95    68.9 2229.32
    94.2 2221.19   119.4 2211.03   128.9 2206.49   145.1 2197.17   148.9 2194.49
   161.5 2182.25   169.9 2175.45   182.8 2158.91   186.7 2152.01   195.3 2131.23
   199.7    2126     204 2124.84   212.6 2125.12   225.5 2123.91   229.8 2122.54
   235.3 2119.67   238.4 2118.34     247 2116.81   251.3 2117.17   258.52119.162
   281.4 2120.15   298.7 2119.87   312.3 2121.66   363.5 2127.77   441.8 2142.67
#Mann= 5 ,-1 , 0
       0      .1       0   161.5     .06       0   235.3    .045       0
   258.5     .06       0   312.3    .055       0
#XS Ineff= 2 , 0
             2202121.114     275        2121.114
Permanent Ineff=
       F       F
Bank Sta=235.3,258.5
XS Rating Curve= 0 ,0
Exp/Cntr(USF)=0,0
Exp/Cntr=0.5,0.3

Type RM Length L Ch R = 1 ,2093    ,83.7,82.5,80.8
XS GIS Cut Line= 4
 2487889.4497822651452.5926396222487755.59984789 651506.23478887
2487606.93446283651574.1815112512487533.36808672651594.105738114
#Sta/Elev= 30
       0 2233.29    11.5 2228.69    19.2 2224.52    28.5 2223.18    37.4 2218.35
    54.6 2210.98    67.6 2207.03    83.8 2203.14    97.7 2196.84     102 2192.77
   119.3 2173.09   123.8 2164.41   127.9 2157.87   130.2 2153.34   133.1 2147.36
   140.8 2129.36   145.1 2122.87   148.4 2121.91   167.1 2120.58   171.5 2119.73
   174.92117.963   180.3 2115.91   184.3 2115.79   193.9  2117.8   202.3 2118.44
   215.5 2117.69   280.5  2124.2   299.3  2126.7   353.4 2136.37   383.9 2140.38
#Mann= 5 ,-1 , 0
       0      .1       0   148.4     .06       0   174.9    .045       0
   193.9     .06       0   280.5    .055       0
Bank Sta=174.9,193.9
XS Rating Curve= 0 ,0
Exp/Cntr(USF)=0,0
Exp/Cntr=0.5,0.3

Type RM Length L Ch R = 1 ,2011    ,88.8,89,89
XS GIS Cut Line= 4
2487829.56369149651361.549441883 2487700.7486396651438.453950475
2487643.07025816651476.906204772 2487524.8295762651549.004181577
#Sta/Elev= 30
       0 2227.18    12.6  2221.7    21.9 2216.81      26 2215.07    35.1 2213.71
    45.2 2209.42    59.2 2204.88      73 2198.89    82.5 2193.64    99.3 2181.54
   105.8 2176.17     111  2170.1   115.1 2164.34   122.6 2156.95   124.4 2154.84
   128.5  2146.8   133.7 2137.68     143 2123.55     146 2120.65   147.7 2119.56
   148.9 2119.36   166.9 2118.99   176.5 2115.85   186.9 2115.22   195.1 2113.94
   206.6 2115.61   247.2  2118.1   282.1 2124.65   317.1 2131.52   357.8 2137.69
#Mann= 5 ,-1 , 0
       0      .1       0   166.9     .06       0   186.9    .045       0
   206.6     .06       0   282.1    .055       0
Bank Sta=186.9,206.6
XS Rating Curve= 0 ,0
Exp/Cntr(USF)=0,0
Exp/Cntr=0.3,0.1

Type RM Length L Ch R = 1 ,1922    ,142.6,138.2,132.7
XS GIS Cut Line= 4
2487773.44136993651317.9023118932487686.25479058651344.542655582
2487548.20937329651431.7292349292487482.81943877651509.228416571
#Sta/Elev= 30
       0 2215.57    11.2  2214.4    22.2 2211.39    44.4 2204.33    58.1 2199.01
    63.8 2196.12    78.1    2185    86.2 2176.97    95.3 2171.59    98.3 2167.51
     100 2164.54   103.1 2157.32   114.2 2128.43     118 2120.43     119 2118.95
   123.7 2116.72   142.6 2116.02  150.462114.632  154.672112.881   156.8 2111.95
     163 2111.05  175.62 2112.88   207.9 2113.92   222.9 2113.22  259.252119.004
   280.4 2124.29   308.8 2133.36   314.5 2134.35   328.7 2135.22355.8387 2139.56
#Mann= 5 ,-1 , 0
       0      .1       0  150.46     .06       0  154.67    .045       0
  175.62     .06       0  259.25    .055       0
Bank Sta=154.67,175.62
XS Rating Curve= 0 ,0
Exp/Cntr(USF)=0,0
Exp/Cntr=0.3,0.1

Type RM Length L Ch R = 1 ,1784    ,116.5,119.1,119.2
XS GIS Cut Line= 4
2487676.56739288 651175.013195742487555.47492156651245.246829103
2487470.71019164651368.7611498452487427.11690197651436.572933782
#Sta/Elev= 30
       0 2219.88    15.9 2215.82    39.6 2206.15      51  2200.7    66.8 2189.98
    77.22178.934    80.7 2175.47    87.5 2170.63      90 2168.39      92 2165.69
    94.9 2160.84   106.6 2135.65   109.5 2130.25   127.1 2114.26   151.7 2113.29
   166.2 2111.77  186.942106.844   190.5  2105.9   200.2  2105.3   204.9  2105.7
   210.7 2107.08   214.8 2107.22     228 2106.44   253.9 2108.89   263.3 2108.75
   268.3 2109.52   292.3 2116.23   344.6 2133.24   354.1 2135.66370.4041 2138.35
#Mann= 4 ,-1 , 0
       0      .1       0    77.2     .06       0  186.94    .045       0
   214.8    .055       0
Bank Sta=186.94,214.8
XS Rating Curve= 0 ,0
Exp/Cntr(USF)=0,0
Exp/Cntr=0.3,0.1

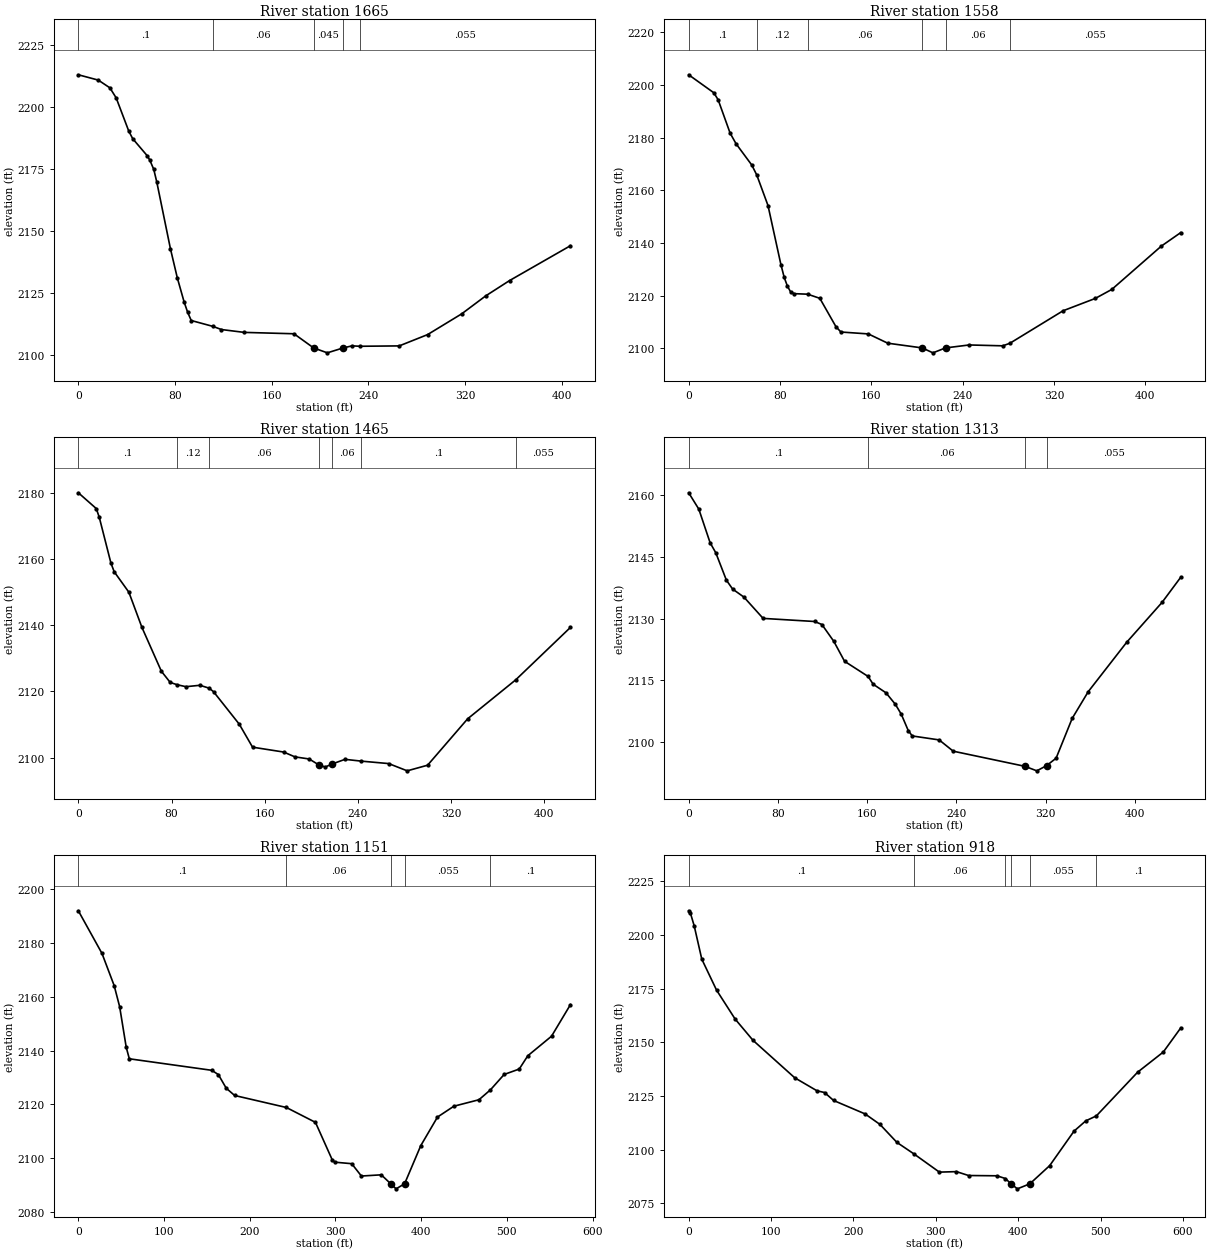
Type RM Length L Ch R = 1 ,1665    ,105.3,106.1,106.7
XS GIS Cut Line= 4
2487586.95896411651087.8266163932487465.86649279651187.122442872
2487366.57066631651291.2619682032487298.75888238651373.604848698
#Sta/Elev= 30
       0 2212.83    16.5 2210.69    26.1 2207.58    31.3 2203.55    41.7 2190.21
      45 2187.12    57.2 2180.16    59.2 2178.42    62.4  2174.8    64.9 2169.72
    76.2 2142.87    81.9 2131.14    87.6 2121.34    90.4  2117.4    93.4 2114.02
  111.242111.671   118.4 2110.39   137.3 2109.24   178.4 2108.69  194.69 2102.99
     206 2101.02  219.05 2102.99   226.5 2103.83  232.922103.662   265.5 2103.81
   288.9 2108.34   317.2 2116.71     337 2123.91   356.8 2130.09 407.161  2144.1
#Mann= 5 ,-1 , 0
       0      .1       0  111.24     .06       0  194.69    .045       0
  219.05     .06       0  232.92    .055       0
Bank Sta=194.69,219.05
XS Rating Curve= 0 ,0
Exp/Cntr(USF)=0,0
Exp/Cntr=0.3,0.1

Type RM Length L Ch R = 1 ,1558    ,93.9,93.5,89.3
XS GIS Cut Line= 4
2487526.41272845651000.6400370462487415.00765484651095.092164672
2487281.80593639651218.6064854142487226.10339959651305.793064761
#Sta/Elev= 30
       0 2203.86      22 2197.04    25.8 2194.39    36.3 2181.72    41.5 2177.69
    55.3  2169.6   59.692165.792    69.5 2154.24    80.8 2131.84    83.7 2126.96
    86.5 2123.65    89.3 2121.48    92.2  2120.8  104.232120.595   114.9 2119.03
   129.1 2108.21   133.4 2106.24   157.4 2105.52   174.4    2102  204.592100.212
     214 2098.34  225.012100.212   245.8 2101.33   275.2    2101   281.42101.967
     328  2114.3   356.2 2118.98   370.7  2122.4   414.1 2138.84431.1721 2143.99
#Mann= 6 ,-1 , 0
       0      .1       0   59.69     .12       0  104.23     .06       0
  204.59    .045       0  225.01     .06       0   281.4    .055       0
Bank Sta=204.59,225.01
XS Rating Curve= 0 ,0
Exp/Cntr(USF)=0,0
Exp/Cntr=0.3,0.1

Type RM Length L Ch R = 1 ,1465    ,147.5,151.7,110.8
XS GIS Cut Line= 4
2487453.75724566650918.2971565522487344.77402148651024.858531309
2487230.94709844 651155.638400332487180.08826049651237.981280825
#Sta/Elev= 30
       0 2179.94    15.4 2175.18      18 2172.51      28 2158.71    30.8 2156.11
    43.4 2149.94    54.6 2139.33    71.3  2126.1    78.9 2122.72   84.992122.013
    92.4 2121.44   104.4 2121.86  112.382120.988   116.1 2119.92   138.2 2110.12
   149.6 2103.19   176.3 2101.72     186 2100.26   198.2 2099.63   206.3 2097.89
     212 2097.19   217.7 2098.09     229 2099.52  242.942098.979   266.5 2098.24
   282.4 2096.05   299.9 2097.75   334.3 2111.75  375.582123.506422.5838 2139.33
#Mann= 7 ,-1 , 0
       0      .1       0   84.99     .12       0  112.38     .06       0
   206.3    .045       0   217.7     .06       0  242.94      .1       0
  375.58    .055       0
Bank Sta=206.3,217.7
XS Rating Curve= 0 ,0
Exp/Cntr(USF)=0,0
Exp/Cntr=0.3,0.1

Type RM Length L Ch R = 1 ,1313    ,160.1,162.4,163.8
XS GIS Cut Line= 4
2487359.30511803650799.6265346622487240.63449614650954.624897946
2487155.86976622651080.5610681142487102.58907884651158.060249756
#Sta/Elev= 30
       0 2160.47     9.1  2156.5    19.2 2148.37    24.3 2145.93    33.8  2139.3
    39.4 2137.14    49.5  2135.2    66.7 2130.04   112.8 2129.29   119.4 2128.56
   130.1 2124.47   139.7 2119.65  160.852115.969   165.3  2114.1   176.8 2112.02
   185.2 2109.24   190.5 2106.85   196.8 2102.86   200.4 2101.56   224.5  2100.6
   237.1 2097.87   301.6 2094.19     312 2093.11   320.7 2094.36   329.3 2096.17
   343.7 2105.81   358.1 2112.29   392.6 2124.27   424.3 2133.93 441.064 2140.03
#Mann= 4 ,-1 , 0
       0      .1       0  160.85     .06       0   301.6    .045       0
   320.7    .055       0
Bank Sta=301.6,320.7
XS Rating Curve= 0 ,0
Exp/Cntr(USF)=0,0
Exp/Cntr=0.3,0.1

Type RM Length L Ch R = 1 ,1151    ,231.7,233.3,235.1
XS GIS Cut Line= 4
2487319.75415012650676.8142955562487124.11626017650872.452185503
2487020.76039378650979.499332833 2486891.5655608651053.324951681
#Sta/Elev= 30
       0 2191.98    27.6 2176.12    41.8 2164.18    48.2 2156.34    55.9 2141.21
    59.5 2136.96   155.7 2132.68   163.4 2131.08   172.6 2126.02   182.4 2123.32
  242.73 2118.86   276.7 2113.33   296.3 2099.38   299.2 2098.53     319 2097.97
   330.3 2093.38   353.5 2093.83  364.532090.506   370.8 2088.62  380.732090.508
   399.6 2104.68   419.1  2115.3   438.2 2119.33   467.5 2121.74  480.942125.433
   496.9 2131.14   514.5 2133.15   524.5 2138.09   552.2 2145.36574.2744 2157.11
#Mann= 5 ,-1 , 0
       0      .1       0  242.73     .06       0  364.53    .045       0
  380.73    .055       0  480.94      .1       0
Bank Sta=364.53,380.73
XS Rating Curve= 0 ,0
Exp/Cntr(USF)=0,0
Exp/Cntr=0.3,0.1

Type RM Length L Ch R = 1 ,918     ,214.6,229.5,242.3
XS GIS Cut Line= 4
2487260.69365504650551.3107435142487042.90807944650665.740452728
2486847.27018949 650806.009128542486747.60560405650853.995780791
#Sta/Elev= 30
       0  2211.3     2.2 2210.09     6.7 2204.29    15.9 2188.77    33.8 2174.35
    56.4 2160.83    78.1 2150.92   128.7 2133.48   155.8  2127.4   164.9 2126.61
   175.9  2122.9   214.1 2116.64   232.2 2111.74   252.7 2103.38   273.62097.952
   304.3 2089.51     325 2089.74   339.7 2087.93   374.2  2087.8  384.512086.512
  391.232084.062     399 2081.72  414.132084.063   438.2 2092.54   467.7 2108.59
     482  2113.4  494.842115.712     545  2136.1   576.1 2145.47  597.36 2156.75
#Mann= 6 ,-1 , 0
       0      .1       0   273.6     .06       0  384.51    .055       0
  391.23    .045       0  414.13    .055       0  494.84      .1       0
Bank Sta=391.23,414.13
XS Rating Curve= 0 ,0
Exp/Cntr(USF)=0,0
Exp/Cntr=0.5,0.3

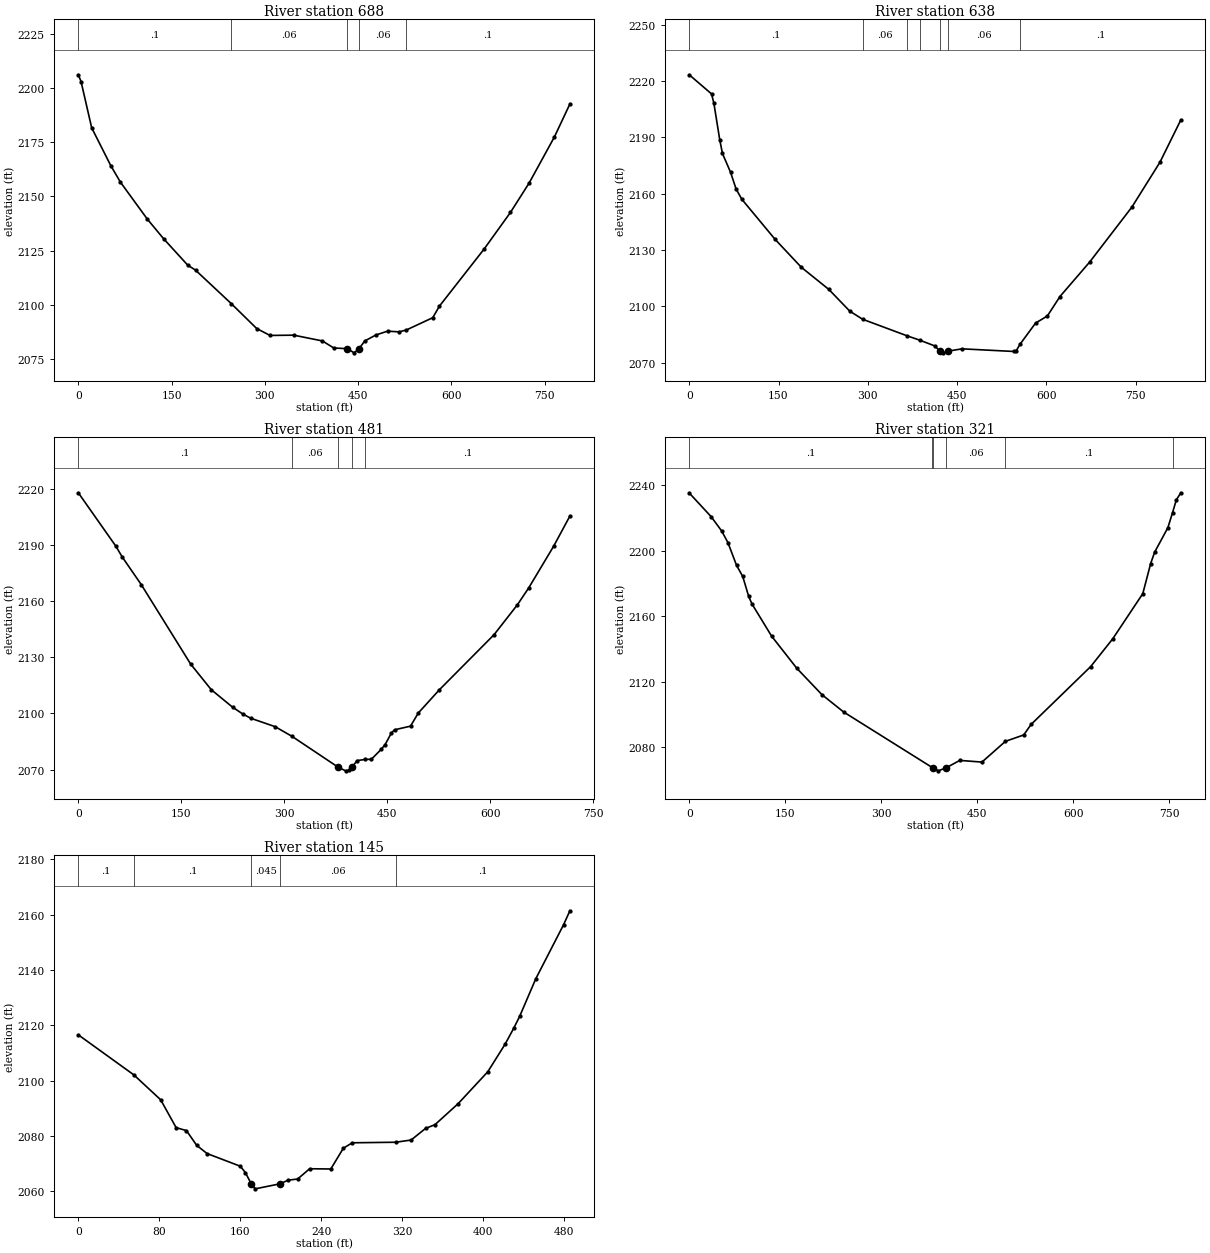
Type RM Length L Ch R = 1 ,688     ,51.7,50.5,50.1
XS GIS Cut Line= 4
2487234.85468844 650499.632810322486906.33068457650625.136362362
2486777.13585159650481.1764056082486596.26308541650647.284048016
#Sta/Elev= 30
       0 2206.03     4.4 2202.93    21.5 2181.61    52.2  2164.2    67.7 2156.59
     111 2139.56   137.1 2130.55   176.1 2118.32   188.5 2116.07  245.86 2100.68
     287 2089.15   308.4 2085.98   346.5 2086.11   392.6 2083.45   410.9  2080.2
  432.852079.888   443.6 2077.97  451.532079.889   460.6 2083.41   478.3 2086.15
   497.4 2087.96   515.9 2087.63  527.562088.481   570.1 2094.16   580.9 2099.51
   652.8 2125.81     695 2142.61   725.1 2156.17   765.6 2177.31790.6863 2192.58
#Mann= 5 ,-1 , 0
       0      .1       0  245.86     .06       0  432.85    .045       0
  451.53     .06       0  527.56      .1       0
#XS Ineff= 2 , 0
             410 2079.79     473         2079.79
Permanent Ineff=
       F       F
Bank Sta=432.85,451.53
XS Rating Curve= 0 ,0
Exp/Cntr(USF)=0,0
Exp/Cntr=0.5,0.3

Type RM Length L Ch R = 1 ,638     ,164,156.3,143.8
XS GIS Cut Line= 4
2487227.47212656 650407.350786762486926.91849688650575.145566036
2486800.80558448 650437.193408062486575.93002264650628.047984753
#Sta/Elev= 30
       0 2223.38    37.5 2213.18    41.4 2208.22    51.2 2188.85    55.8 2181.46
    69.5 2171.39    78.7 2162.53    88.4 2157.05   144.2 2135.74   188.3 2120.85
   234.5 2109.06   269.8 2097.46  291.39 2093.14  366.282084.302  388.06 2081.93
   412.5 2078.95     421 2076.28   426.6 2075.26   435.1 2076.18   458.4 2077.39
   545.1    2076   549.6 2076.43  555.572079.718     582 2091.12   601.8  2094.9
     623 2105.27   672.9 2123.63   743.8 2152.89   790.9 2176.75826.0783 2199.33
#Mann= 7 ,-1 , 0
       0      .1       0  291.39     .06       0  366.28      .1       0
  388.06     .06       0     421    .045       0   435.1     .06       0
  555.57      .1       0
Bank Sta=421,435.1
XS Rating Curve= 0 ,0
Exp/Cntr(USF)=0,0
Exp/Cntr=0.5,0.3

Type RM Length L Ch R = 1 ,481     ,160.3,159.8,158.9
XS GIS Cut Line= 4
2487145.46532287 650211.289879412486879.47083947650338.566809639
2486743.61344204650421.5113259682486550.55292989650598.840981569
#Sta/Elev= 30
       0 2217.73    54.7 2189.22    63.9  2183.5    91.7 2168.72   163.7 2126.28
   193.7 2112.62   224.7 2103.29     240 2099.56   251.3 2097.36   286.8 2092.87
  311.122087.762  378.672071.223   389.5  2069.3   394.1 2069.61  398.552071.222
   406.2 2074.77  418.392075.417     427 2075.47   441.1 2080.72     447 2083.32
   456.1 2089.48   460.7  2091.2     484 2093.16   495.3 2100.16   525.8 2112.48
   605.7 2141.98   639.7 2157.93   656.2 2166.96   692.6 2189.26716.1946 2205.31
#Mann= 5 ,-1 , 0
       0      .1       0  311.12     .06       0  378.67    .045       0
  398.55     .06       0  418.39      .1       0
Bank Sta=378.67,398.55
XS Rating Curve= 0 ,0
Exp/Cntr(USF)=0,0
Exp/Cntr=0.3,0.1

Type RM Length L Ch R = 1 ,321     ,179.2,176.2,166.6
XS GIS Cut Line= 4
 2487070.7501298650037.5913268742486817.69108325650186.680377557
2486678.41052274650280.8418832522486480.27902117650514.283949454
#Sta/Elev= 30
       0 2235.24    34.1 2220.83    50.6 2212.05    60.4 2204.93      74 2190.92
    83.6  2184.2    92.9 2171.97      98 2167.42   128.6 2147.78     168 2128.11
   207.4 2111.94   241.4 2101.32  379.322067.506  380.242067.278     389  2065.4
  401.452067.278   422.7 2071.78   457.3 2070.75  493.962083.425   522.6 2087.35
     534 2093.74   627.2 2129.14   661.7 2146.14   708.6 2173.72   720.9 2192.14
   727.1 2199.06   747.8 2214.06  755.062223.216     761 2231.05768.0231 2235.37
#Mann= 6 ,-1 , 0
       0      .1       0  379.32     .06       0  380.24    .045       0
  401.45     .06       0  493.96      .1       0  755.06      .1       0
Bank Sta=380.24,401.45
XS Rating Curve= 0 ,0
Exp/Cntr(USF)=0,0
Exp/Cntr=0.3,0.1

Type RM Length L Ch R = 1 ,145     ,147.8,145.2,139.6
XS GIS Cut Line= 4
2486743.14655791649959.1234054612486660.75524042650063.093401333
2486541.09166027650259.2632048642486474.39392707650363.233200735
#Sta/Elev= 30
       0 2116.52   54.862102.063    81.4 2093.06    96.7 2082.99   106.9 2081.91
   117.1 2076.56   127.3 2073.62   160.2 2069.03   165.2 2066.73  170.932062.692
   174.9 2060.87  199.45 2062.69   207.4    2064   216.8 2064.42   228.7 2068.13
   249.6 2068.04     262 2075.54   270.8 2077.51  313.772077.708     329 2078.51
   343.3 2082.71   352.6 2084.06   375.5 2091.65   404.8 2103.18   421.8 2113.08
   430.5 2118.94   436.3  2123.2   452.3 2136.83   479.7  2156.3485.9693 2161.35
#Mann= 5 ,-1 , 0
       0      .1       0   54.86      .1       0  170.93    .045       0
  199.45     .06       0  313.77      .1       0
Bank Sta=170.93,199.45
XS Rating Curve= 0 ,0
Exp/Cntr(USF)=0,0
Exp/Cntr=0.3,0.1