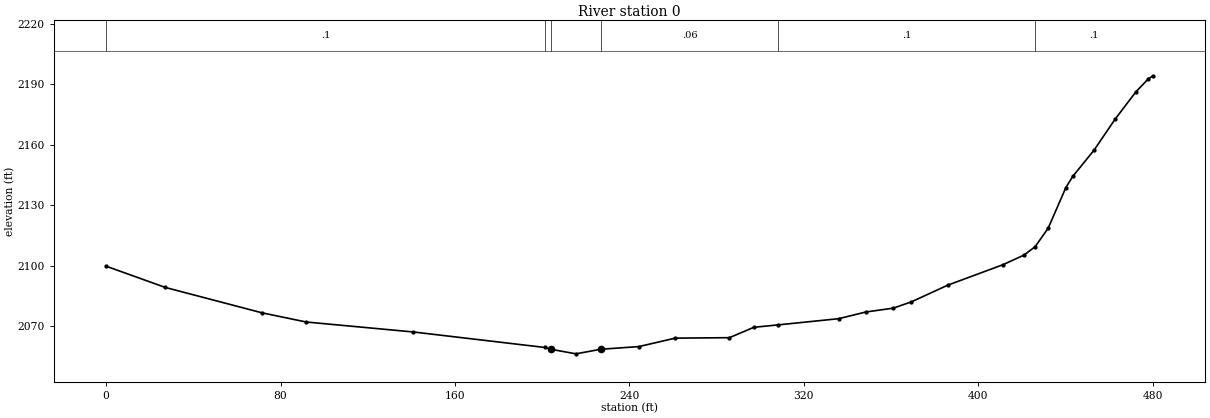
HEC-RAS study SHAVERN.prj: SHAVERN

--- SHAVERN.g01 (geometry) --- (continued)

Type RM Length L Ch R = 1 ,0       ,,,
XS GIS Cut Line= 4
2486515.72915138649831.9082220072486531.28704011 649945.99940603
2486486.34202822650113.6788734582486431.02509051650296.916229616
#Sta/Elev= 30
       0 2099.67    27.2  2089.1    71.6 2076.49    91.8 2071.95   140.9 2067.01
   201.32059.305  203.952058.425   215.5 2056.15  226.932058.426   244.4 2059.76
     261 2063.94   285.9 2064.17   297.1 2069.32  308.212070.523     336  2073.6
   348.5 2076.93     361 2078.82   369.4 2081.98   386.1 2090.27   411.4 2100.42
     421 2105.17   426.12109.326   432.1 2118.55   440.2 2138.68   443.4  2144.3
   453.1 2157.21   462.7 2172.52   472.3 2186.18     478 2192.66   480.2 2194.19
#Mann= 6 ,-1 , 0
       0      .1       0   201.3     .06       0  203.95    .045       0
  226.93     .06       0  308.21      .1       0   426.1      .1       0
Bank Sta=203.95,226.93
XS Rating Curve= 0 ,0
Exp/Cntr(USF)=0,0
Exp/Cntr=0.3,0.1
LCMann Table=0

Chan Stop Cuts=-1
Use User Specified Reach Order=0
Composite Channel Slope=5